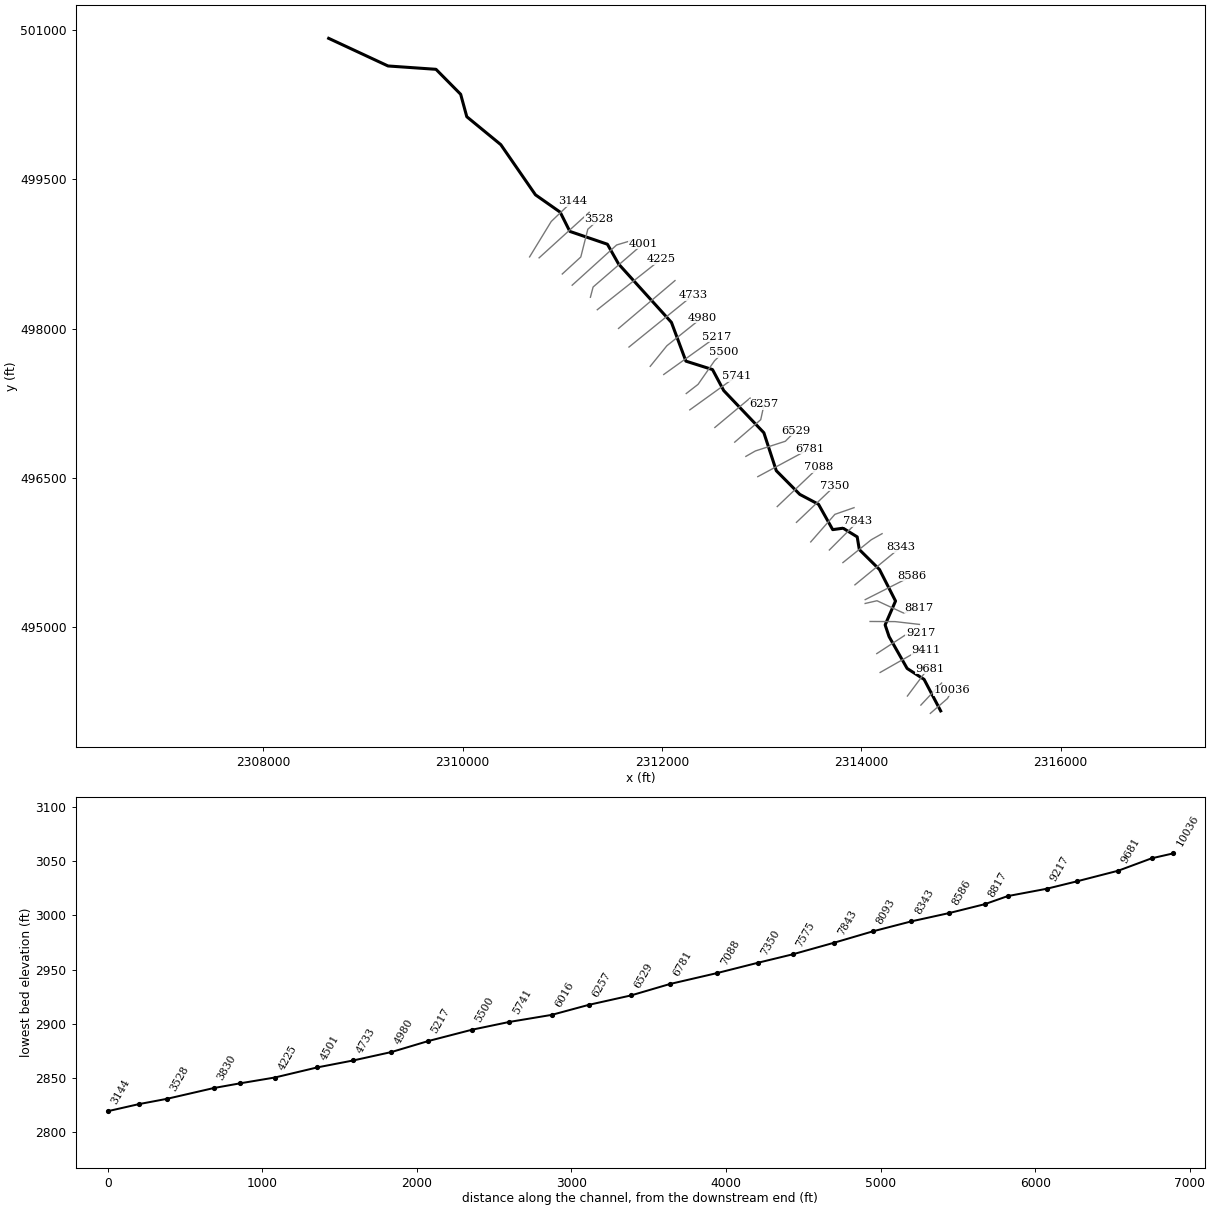
--- STONYRB.prj (project) ---

Proj Title=STONYRB
Current Plan=p01
Default Exp/Contr=0,0
English Units
Geom File=g01
Flow File=f01
Plan File=p01
Background Map Layer=Inundation Boundary (01pct Value_0)
BEGIN DESCRIPTION:
----------MODEL BY WOOD PLC 2021----------
Stream Name: Stony Run
Flood Zone: Approximate
Pocahontas County, WV
HEC-RAS Version: RAS 6.0
Vertical Datum: NAVD88
Projection: NAD 1983 StatePlane West Virginia S FIPS 4702 (US Feet)
Terrain: 1-meter LIDAR (FEMA Region III 3DEP collected 2016-2018)
Land Use: 2019 NLCD
Hydrologic Method:
WV SIR2010-5033 regression equations
Model Notes:
END DESCRIPTION:
DSS Export Rating Curves= 0
DSS Export Rating Curve Sorted= 0
DSS Export Volume Flow Curves= 0
DXF OffsetX= 0
DXF OffsetY= 0
DXF ScaleX= 0
DXF ScaleY= 0

--- STONYRB.p01 (plan) ---

Plan Title=Floodplain
Program Version=6.00
Short Identifier=Floodplain
Geom File=g01
Flow File=f01
Subcritical Flow
K Sum by GR= 0
Std Step Tol= 0.01
Critical Tol= 0.01
Num of Std Step Trials= 20
Max Error Tol= 0.3
Flow Tol Ratio= 0.001
Split Flow NTrial= 30
Split Flow Tol= 0.02
Split Flow Ratio= 0.02
Log Output Level= 0
Friction Slope Method= 1
Unsteady Friction Slope Method= 2
Unsteady Bridges Friction Slope Method= 1
Parabolic Critical Depth
Global Vel Dist= 0 , 0 , 0
Global Log Level= 0
CheckData=True
Encroach Param=-1 ,0,0, 0
Mapping Interval=1HOUR
Computation Time Step Use Courant=        0
Computation Time Step Use Time Series=    0
Computation Time Step Count To Double=0
Computation Time Step Max Doubling=0
Computation Time Step Max Halving=0
Computation Time Step Residence Courant=0
Run HTab= 0
Run UNet= 0
Run Sediment= 0
Run PostProcess= 0
Run WQNet= 0
Run RASMapper=-1
UNET Theta= 0
UNET Theta Warmup= 0
UNET ZTol= 0
UNET ZSATol= 0
UNET MxIter= 0
UNET Max Iter WO Improvement= 0
UNET MaxInSteps= 0
UNET DtIC= 0
UNET DtMin= 0
UNET MaxCRTS= 0
UNET WFStab= 0
UNET SFStab= 0
UNET WFX= 1
UNET SFX= 1
UNET Gravity=32.174
UNET 1D Methodology=Finite Difference
UNET DSS MLevel= 1
UNET Pardiso=0
UNET DZMax Abort= 0
UNET Use Existing IB Tables= 0
UNET Froude Reduction=False
UNET Froude Limit= 0
UNET Froude Power= 0
UNET D1 Cores= 0
UNET WindReference=Eulerian
UNET WindDragFormulation=Hsu (1988)
UNET D2 Coriolis=0
UNET D2 Cores= 0
UNET D2 Theta= 1
UNET D2 Theta Warmup= 1
UNET D2 Z Tol= 0.01
UNET D2 Volume Tol= 0.01
UNET D2 Max Iterations= 20
UNET D2 Equation= 0
UNET D2 RampUpFraction=0.1
UNET D2 TimeSlices= 1
UNET D2 Turbulence Formulation=Non-Conservative (original)
UNET D2 Eddy Viscosity=0.3
UNET D2 Transverse Eddy Viscosity=0.1
UNET D2 Smagorinsky Mixing=0
UNET D2 BCVolumeCheck=0
UNET D2 Cores=0
UNET D2 SolverType=PARDISO (Direct)
UNET D2 Minimum Iterations= 2147483647
UNET D2 Maximum Iterations= 2147483647
UNET D2 Restart Number= 10
UNET D2 Relaxation Coeff=1.3
UNET D2 SOR Precondition Iterations= 10
UNET D2 ILUT Maximum Fill= 8
UNET D2 ILUT Tolerance=1E-08
UNET D1D2 MaxIter= 0
UNET D1D2 ZTol=0.01
UNET D1D2 QTol=0.1
UNET D1D2 MinQTol=1
Write IC File= 0
Write IC File at Fixed DateTime=0
Write IC File at Sim End=0
Echo Input=False
Echo Parameters=False
Echo Output=False
Write Detailed= 0
HDF Write Warmup=0
HDF Write Time Slices=0
HDF Flush=0
HDF Compression= 1
HDF Chunk Size= 1
HDF Spatial Parts= 1
HDF Use Max Rows=0
HDF Fixed Rows= 1
Calibration Method= 0
Calibration Iterations= 20
Calibration Max Change=0.05
Calibration Tolerance=0.2
Calibration Maximum=1.5
Calibration Minimum=0.5
Calibration Optimization Method= 1
WQ AD Non Conservative
WQ ULTIMATE=-1
WQ Max Comp Step=1HOUR
WQ Output Interval=15MIN
WQ Output Selected Increments= 0
WQ Output face flow=0
WQ Output face velocity=0
WQ Output face area=0
WQ Output face dispersion=0
WQ Output cell volume=0
WQ Output cell surface area=0
WQ Output cell continuity=0
WQ Output cumulative cell continuity=0
WQ Output face conc=0
WQ Output face dconc_dx=0
WQ Output face courant=0
WQ Output face peclet=0
WQ Output face adv mass=0
WQ Output face disp mass=0
WQ Output cell mass=0
WQ Output cell source sink temp=0
WQ Output nsm pathways=0
WQ Output nsm derived pathways=0
WQ Create Restart=0
WQ Fixed Restart=0
WQ System Summary=0
WQ Write To DSS=0
Sorting and Armoring Iterations= 10
XS Update Threshold= 0.02
Bed Roughness Predictor= 0
Hydraulics Update Threshold= 0.02
Energy Slope Method= 1
Volume Change Method= 1
Sediment Retention Method= 0
Sediment TS Multiplier= 1
Warm Up Method= 0
XS Weighting Method= 0
Number of US Weighted Cross Sections= 1
Number of DS Weighted Cross Sections= 1
Upstream XS Weight=0
Main XS Weight=1
Downstream XS Weight=0
Number of DS XS's Weighted with US Boundary= 1
Upstream Boundary Weight= 1
Weight of XSs Associated with US Boundary= 0
Number of US XS's Weighted with DS Boundary= 1
Downstream Boundary Weight= 0.5
Weight of XSs Associated with DS Boundary= 0.5
Percentile Method= 0
Sediment Output Level= 3
Mass or Volume Output= 0
Output Increment Type= 1
Profile and TS Output Increment= 1
Transport Output Increment 1
XS Output Flag= 0
XS Output Increment= 10
Read HDF5 Sediment Hotstart= 0
Sediment Hotstart Type= 0
Write Gradation File= 0
Read Gradation Hotstart= 0
Write HDF5 File= 1
Write Binary Output= 1
Write DSS Sediment File= 0
DSS Sediment Output Type= 1
SV Curve= 0
Specific Gage Flag= 0
Subcell Erosion Methods= 0
Subcell Deposition Methods= 0
Advection Scheme= 1
Matrix Solver= 0
Implicit Weighting Factor= 1
Maximum Outer Loop Convergence Iterations= 5
Convergence Maximum Absolute= 0.001
Convergence RMSE= 0.0001
Grain Fractions Max Abs Error= 0.001
Max Subgrid Regions= 1
Max Subgrid Length Scale= 3.402823E+38
Initial Layer Thickness= 3.402823E+38
Min Layer Thickness= 3.402823E+38
Max Layer Thickness= 3.402823E+38
Number of Layers= 5

--- STONYRB.f01 (steady flow) ---

Flow Title=Flow
Program Version=6.00
Number of Profiles= 6
Profile Names=01pct,10pct,04pct,02pct,0_2pct,01plus
River Rch & RM=STONYRB,Main            ,10036
     801     429     567     680    1110    1180
River Rch & RM=STONYRB,Main            ,6257
     925     498     657     787    1280    1370
Boundary for River Rch & Prof#=STONYRB,Main            , 1
Up Type= 0
Dn Type= 3
Dn Slope=0.026778
Boundary for River Rch & Prof#=STONYRB,Main            , 2
Up Type= 0
Dn Type= 3
Dn Slope=0.026778
Boundary for River Rch & Prof#=STONYRB,Main            , 3
Up Type= 0
Dn Type= 3
Dn Slope=0.026778
Boundary for River Rch & Prof#=STONYRB,Main            , 4
Up Type= 0
Dn Type= 3
Dn Slope=0.026778
Boundary for River Rch & Prof#=STONYRB,Main            , 5
Up Type= 0
Dn Type= 3
Dn Slope=0.026778
Boundary for River Rch & Prof#=STONYRB,Main            , 6
Up Type= 0
Dn Type= 3
Dn Slope=0.026778
DSS Import GetInterval= 0
DSS Import GetPeak= 0
DSS Import FillOption= 0

--- STONYRB.g01 (geometry) ---

Geom Title=Geometry
Program Version=6.10

River Reach=STONYRB         ,Main
Reach XY= 30
 2314797.0574185494154.191960559     2314630.824      494471.164
     2314460.496      494581.217     2314279.233      494901.753
     2314239.861      495019.153     2314344.171      495259.362
     2314183.464      495575.619     2313980.823      495776.855
     2313959.507      495904.291      2313818.12      495991.719
       2313713.7        495977.3     2313571.368      496232.176
     2313383.434      496331.796     2313147.702      496569.756
     2313023.061      496951.429      2312620.32      497375.647
     2312507.806      497587.007     2312240.772      497671.689
     2312095.497      498061.544     2311565.426      498648.413
      2311453.08        498847.6     2311076.031      498976.606
     2310979.323      499169.853     2310731.196      499344.436
     2310383.276      499849.138     2310042.122      500129.905
     2309980.571       500355.75     2309733.008      500606.749
      2309251.68      500640.337     2308656.094      500918.231

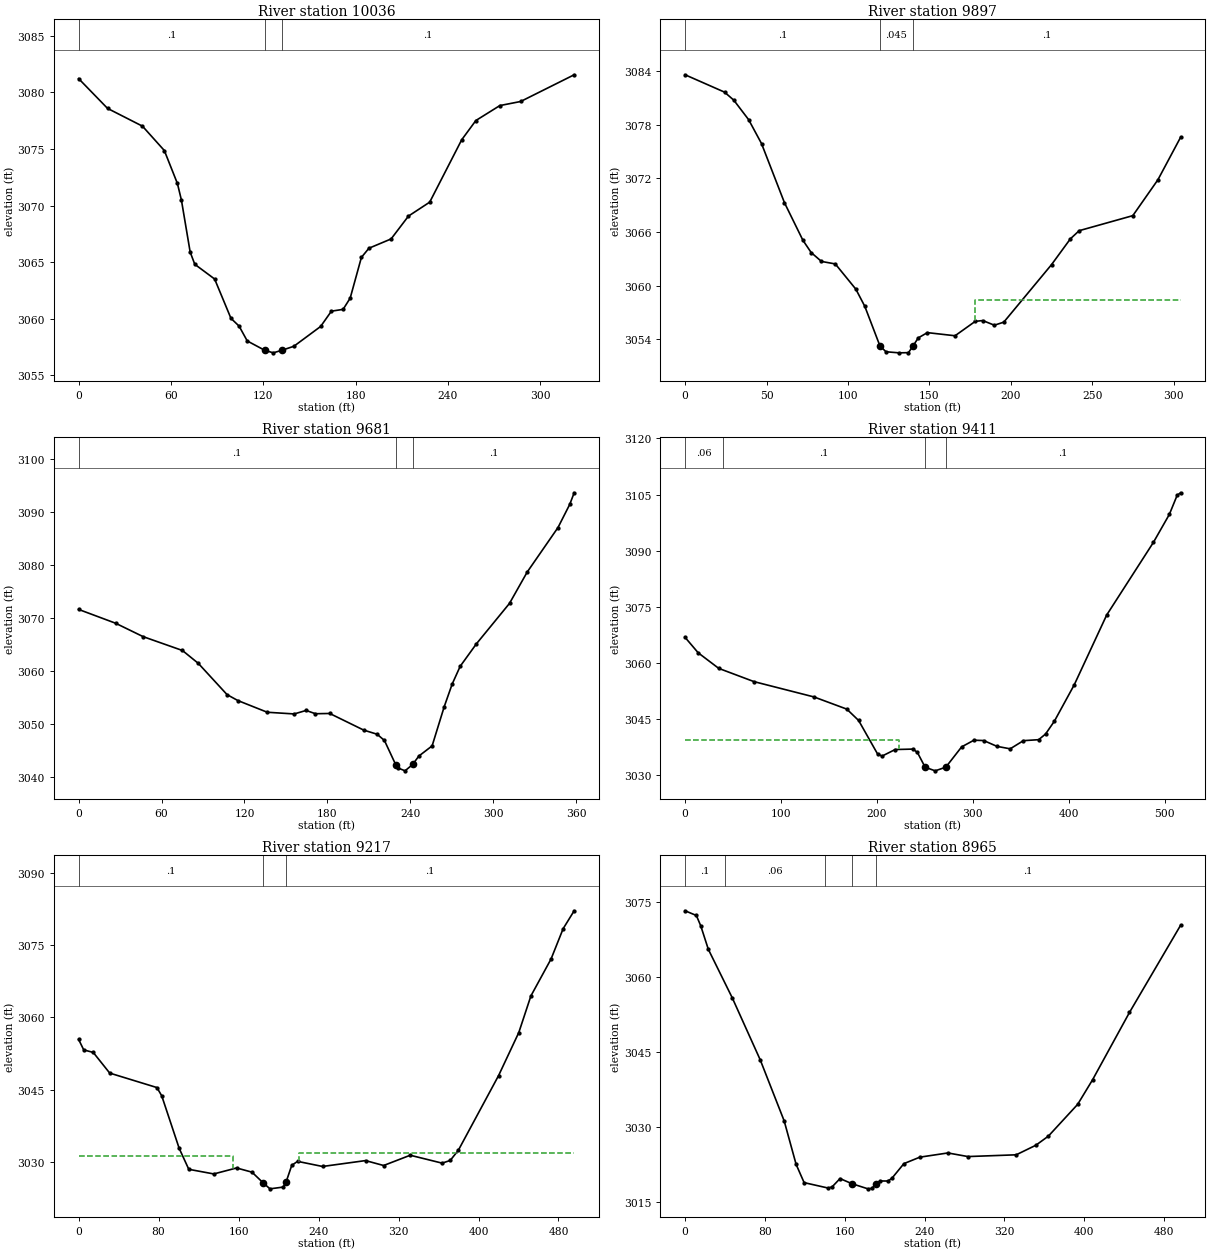
Type RM Length L Ch R = 1 ,10036   ,137.9,139.1,140.7
XS GIS Cut Line= 3
2314693.47135448494129.371143748 2314865.6739278 494279.08851897
2314912.00132798494360.817726301
#Sta/Elev= 30
       0 3081.22    18.8 3078.59    41.5 3077.02    55.7 3074.87    64.2 3071.96
    66.8  3070.5    72.5  3065.9    75.5 3064.82    88.4 3063.52      99 3060.05
   104.3 3059.36   109.6 3058.05   120.9 3057.23   126.5    3057   132.2 3057.23
   139.9 3057.58   157.3 3059.33   164.3 3060.68   171.9 3060.84   176.5 3061.83
   183.8 3065.43   188.7 3066.24   203.1 3067.06   214.4 3069.08   228.2 3070.31
     249 3075.82   258.2 3077.52   273.8 3078.84   287.3  3079.2   322.1 3081.56
#Mann= 3 ,-1,0
       0      .1       0   120.9    .045       0   132.2      .1       0
Bank Sta=120.9,132.2
XS Rating Curve= 0 ,0
Exp/Cntr=0.3,0.1

Type RM Length L Ch R = 1 ,9897    ,215.7,215.1,213.9
XS GIS Cut Line= 2
2314598.38075962494212.7112545032314806.40413162494434.602851302
#Sta/Elev= 30
       0 3083.58    24.2 3081.64    29.9 3080.74      39 3078.56    46.9 3075.89
      61 3069.27    72.3 3065.08    77.4  3063.7    83.7 3062.71    92.2 3062.43
   104.8 3059.61   110.3 3057.69   119.6 3053.26   123.3 3052.61   131.3 3052.49
   137.1 3052.51  139.84 3053.24   143.1 3054.16   148.7 3054.75   165.7  3054.4
   178.1 3056.01   182.7  3056.1   189.8 3055.58   195.6 3055.92   224.9 3062.35
   236.5 3065.24   241.9 3066.15   274.8 3067.83   290.2 3071.84304.1539  3076.6
#Mann= 3 ,-1,0
       0      .1       0   119.6    .045       0  139.84      .1       0
#XS Ineff= 2 , 0
                          178.03         3058.36
Permanent Ineff=
       F       F
Bank Sta=119.6,139.84
XS Rating Curve= 0 ,0
Exp/Cntr(USF)=0,0
Exp/Cntr=0.3,0.1

Type RM Length L Ch R = 1 ,9681    ,276.3,270.5,263.9
XS GIS Cut Line= 3
2314463.31630939494303.759165146 2314629.1320407 494526.25372824
2314689.42867026494580.520694849
#Sta/Elev= 30
       0 3071.58    26.7 3068.98    46.7 3066.44    75.1 3063.83    86.6  3061.4
   107.4  3055.5   115.2 3054.38   136.5 3052.17     156 3051.85   164.6 3052.51
   171.4 3051.89   181.7 3051.94   206.3  3048.8     216 3048.02   221.3 3046.84
  229.44 3042.28   231.2 3041.65   236.2 3041.11   241.7 3042.31   246.2  3043.9
   255.8 3045.82   264.6 3053.25   270.3 3057.48   276.1 3060.84   287.8 3065.07
   311.8 3072.72   324.6 3078.63   346.9 3087.04   355.4 3091.41   358.6  3093.6
#Mann= 3 ,-1,0
       0      .1       0  229.44    .045       0   241.7      .1       0
Bank Sta=229.44,241.7
XS Rating Curve= 0 ,0
Exp/Cntr(USF)=0,0
Exp/Cntr=0.3,0.1

Type RM Length L Ch R = 1 ,9411    ,192.4,193.5,194.4
XS GIS Cut Line= 3
2314189.71896661494540.8878330422314524.81887155494731.865235056
 2314651.6173024494764.237684592
#Sta/Elev= 30
       0 3066.84    13.7 3062.71    35.1 3058.56    71.9 3055.02   134.3 3050.94
   168.6 3047.68   180.9 3044.65   200.8 3035.64   205.4 3035.15     219 3036.89
   237.6 3037.01   242.2  3036.1  250.23 3032.17   260.7  3031.2   271.8 3032.18
   288.3  3037.6   301.1 3039.38   311.3 3039.29   325.1 3037.74   338.9 3037.08
   352.7 3039.26   368.6 3039.52   375.8 3041.04     385 3044.47   405.7 3054.18
   439.5 3072.81   488.2 3092.21   504.8 3099.67     513 3104.81   516.6 3105.46
#Mann= 4 ,-1,0
       0     .06       0      40      .1       0  250.23    .045       0
   271.8      .1       0
#XS Ineff= 2 , 0
           223.1 3039.55
Permanent Ineff=
       F       F
Bank Sta=250.23,271.8
XS Rating Curve= 0 ,0
Exp/Cntr=0.3,0.1

Type RM Length L Ch R = 1 ,9217    ,257.3,252.5,242
XS GIS Cut Line= 3
2314155.90936924494730.3648497882314439.60956047494915.638444062
2314595.10704138494936.316300565
#Sta/Elev= 30
       0 3055.42     5.1 3053.25    14.6 3052.73    31.1 3048.44    78.3 3045.44
    83.1 3043.74   100.6 3032.82   110.2 3028.48   135.2 3027.52     158 3028.76
   173.4 3027.89   184.3 3025.73   191.4 3024.43   204.5 3024.79   207.4 3025.77
   213.2 3029.31     219 3030.13     244 3029.07     287 3030.29   305.1 3029.27
   331.7  3031.4   363.6 3029.76   371.7 3030.32   379.8 3032.42   420.1 3047.93
   440.3 3056.85   452.4 3064.44   472.6 3072.12   484.7 3078.41   495.7 3082.11
#Mann= 3 ,-1,0
       0      .1       0   184.3    .045       0   207.4      .1       0
#XS Ineff= 2 , 0
          154.08 3031.17  220.56         3031.87
Permanent Ineff=
       F       F
Bank Sta=184.3,207.4
XS Rating Curve= 0 ,0
Exp/Cntr(USF)=0,0
Exp/Cntr=0.3,0.1

Type RM Length L Ch R = 1 ,8965    ,156.5,148,141.5
XS GIS Cut Line= 3
2314088.84661418495053.584320506 2314339.8248952495052.263113715
2314583.94893916495024.105968274
#Sta/Elev= 30
       0 3073.15    11.3 3072.21    15.7 3070.14    23.3 3065.45    47.3 3055.77
    75.3 3043.41    99.3 3031.23   111.3 3022.54   119.3 3018.91   143.3 3017.83
   147.3 3018.05   155.3 3019.72   167.3 3018.69   183.3 3017.67   187.3 3017.77
   191.3 3018.68   195.3 3019.24   203.3 3019.23   207.3 3019.78   219.3  3022.7
   235.3 3023.99   263.4 3024.83   283.5 3024.11   331.9 3024.46   351.6 3026.37
   364.1 3028.18   393.5 3034.53   408.4 3039.42   445.4 3052.86   496.7 3070.27
#Mann= 5 ,-1,0
       0      .1       0      40     .06       0     140      .1       0
   167.3    .045       0   191.3      .1       0
Bank Sta=167.3,191.3
XS Rating Curve= 0 ,0
Exp/Cntr=0.3,0.1

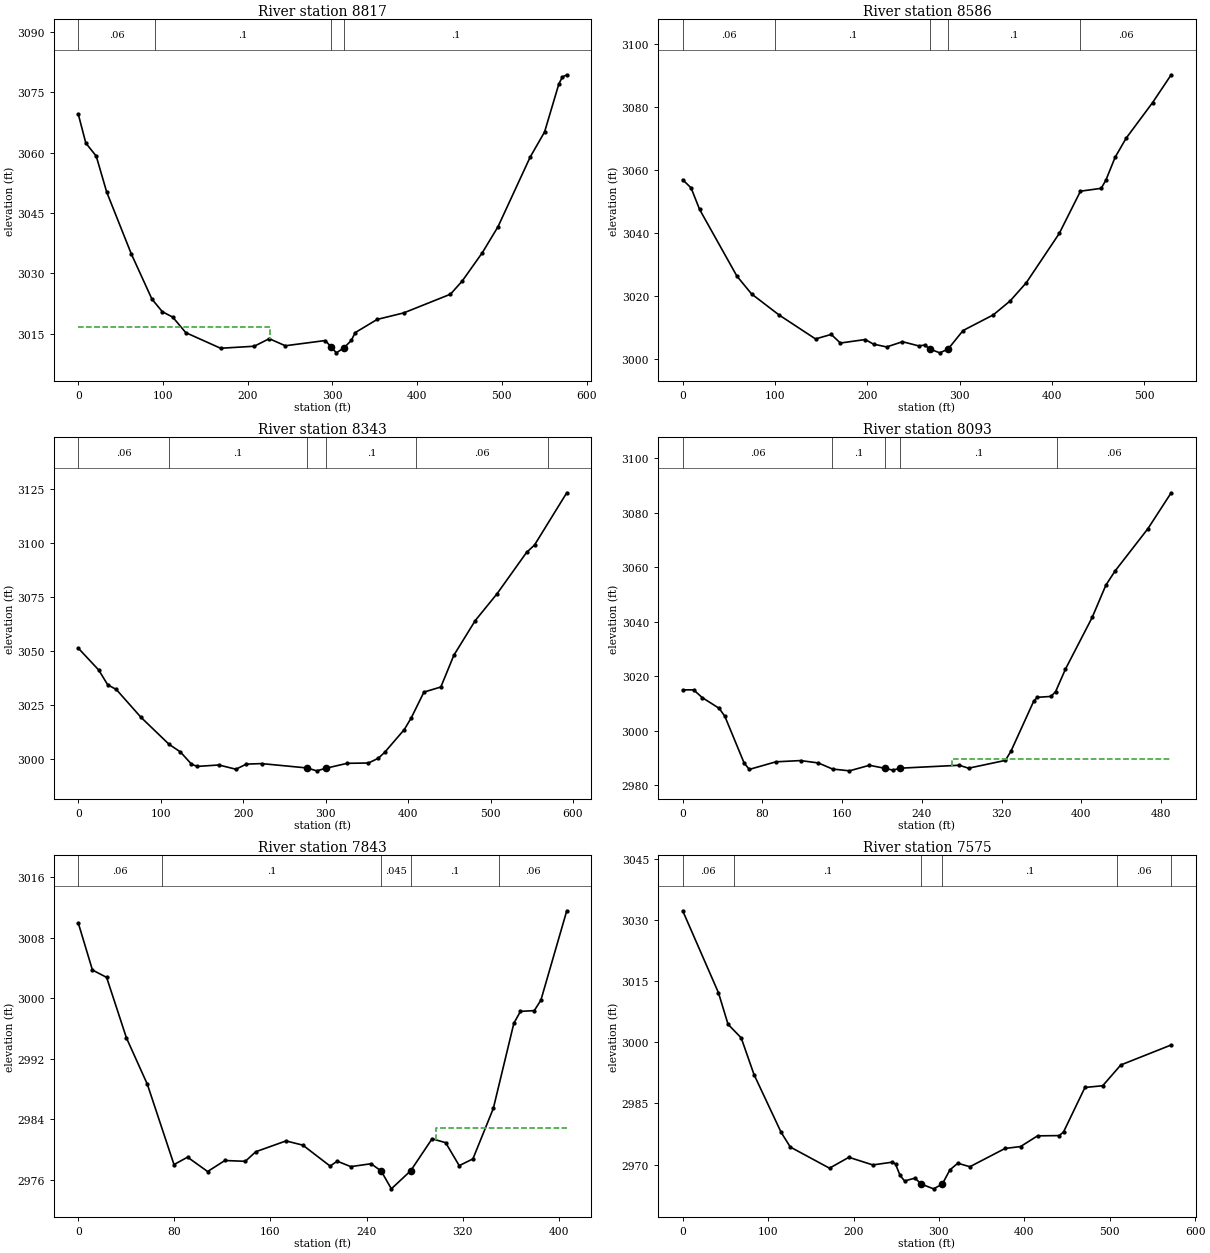
Type RM Length L Ch R = 1 ,8817    ,218.9,230.5,242.5
XS GIS Cut Line= 4
2314039.52718261495234.7461130862314158.17167431495262.049241798
2314424.66788893495138.4783713322314576.98485645495190.975619763
#Sta/Elev= 30
       0 3069.59     8.9 3062.39    21.2 3059.15    33.5 3050.24    62.6 3034.83
    86.9 3023.61    99.2 3020.46   111.5 3019.11   126.9 3015.25     168 3011.37
   207.7 3011.87   225.4 3013.75   244.4 3011.99   291.5 3013.29   298.6 3011.67
   304.6 3010.23   313.7 3011.48   322.4 3013.35   326.8 3015.25   352.8 3018.54
   384.1 3020.16   439.3 3024.81   453.1 3028.06     477 3035.16   495.4 3041.58
   533.4 3058.91   550.4 3065.16   567.3 3077.13   571.4 3078.82   576.6 3079.38
#Mann= 4 ,-1,0
       0     .06       0      90      .1       0   298.6    .045       0
   313.7      .1       0
#XS Ineff= 2 , 0
           225.8  3016.6
Permanent Ineff=
       F       F
Bank Sta=298.6,313.7
XS Rating Curve= 0 ,0
Exp/Cntr(USF)=0,0
Exp/Cntr=0.3,0.1

Type RM Length L Ch R = 1 ,8586    ,240.4,243.6,247.4
XS GIS Cut Line= 2
2314039.85088041 495273.23162237 2314511.8392648495512.629576953
#Sta/Elev= 30
       0 3056.96     9.1 3054.37    18.3 3047.54    58.7  3026.4    74.6 3020.74
   104.4 3014.06   143.9 3006.46   160.9 3007.89   170.8 3005.16   197.7 3006.27
   206.7 3004.81     221 3003.92   238.1 3005.58   255.7 3004.25   262.1 3004.51
     268 3003.25   278.4 3002.05   287.4 3003.21   303.7 3009.12   336.5  3014.1
   354.7 3018.51   372.2 3024.28   407.9 3039.91   430.9 3053.33   453.4 3054.24
   458.5 3056.87   468.5 3064.11   480.3  3070.1   509.1 3081.46   529.2 3090.26
#Mann= 5 ,-1,0
       0     .06       0     100      .1       0     268    .045       0
   287.4      .1       0     430     .06       0
Bank Sta=268,287.4
XS Rating Curve= 0 ,0
Exp/Cntr=0.3,0.1

Type RM Length L Ch R = 1 ,8343    ,249.8,250,250.6
XS GIS Cut Line= 2
2313936.60342133495421.8625799552314393.84216871495798.545617499
#Sta/Elev= 30
       0 3051.18    24.8 3041.05    35.7 3034.22    46.1 3032.07    75.9 3019.24
     110 3006.73   123.8 3003.18   137.3 2997.52   144.1 2996.47   170.5 2997.14
   191.2 2995.17   203.8 2997.54   222.3 2997.78   277.7 2995.75   289.1 2994.43
   300.9 2995.68   326.1 2997.91   351.9 2998.05   363.8 3000.24   371.5 3002.96
   395.3 3013.49   403.7 3018.86   419.2 3030.85   439.7 3033.21   455.5 3047.92
   481.4 3063.93   507.9 3076.36   543.6 3095.44   553.3 3098.88   592.4 3123.04
#Mann= 6 ,-1,0
       0     .06       0     110      .1       0   277.7    .045       0
   300.9      .1       0     410     .06       0     570      .1       0
Bank Sta=277.7,300.9
XS Rating Curve= 0 ,0
Exp/Cntr(USF)=0,0
Exp/Cntr=0.3,0.1

Type RM Length L Ch R = 1 ,8093    ,245.6,249.3,250
XS GIS Cut Line= 3
 2313816.1213934495645.7755581852314101.11860339495875.697564947
2314209.26706869495936.654765389
#Sta/Elev= 30
       0 3014.95      11 3014.95    19.5 3012.13    36.6 3008.17    42.3 3005.24
    61.7 2988.04    66.9 2985.74    93.5 2988.52   118.3 2988.98   136.2  2988.1
   150.4 2985.87   167.4 2985.21   187.4 2987.25   202.9 2986.14   210.8 2985.48
   218.6 2986.19   277.6 2987.26   286.9 2986.18   323.9 2989.05   329.6 2992.52
   352.3 3010.78   355.8 3012.21   369.7 3012.54   374.3 3014.32   384.2 3022.59
     411 3041.56   424.8 3053.45   434.1 3058.67     467 3074.18   490.3 3087.33
#Mann= 5 ,-1,0
       0     .06       0     150      .1       0   202.9    .045       0
   218.6      .1       0  376.18     .06       0
#XS Ineff= 2 , 0
                          270.76         2989.52
Permanent Ineff=
       F       F
Bank Sta=202.9,218.6
XS Rating Curve= 0 ,0
Exp/Cntr=0.3,0.1

Type RM Length L Ch R = 1 ,7843    ,264.8,268.6,266.4
XS GIS Cut Line= 2
2313680.18665481495772.4501058622313967.23728281496060.635321332
#Sta/Elev= 30
       0 3009.95    11.8 3003.73    23.6 3002.76    40.1 2994.75    57.5 2988.62
    79.7 2977.99      91 2978.97   107.7 2977.07   122.1 2978.53   139.1 2978.42
   147.8 2979.69     173 2981.12     187 2980.56   209.7 2977.79   215.6 2978.44
   226.9 2977.72   243.8  2978.1   252.2 2977.14   260.7 2974.78  276.77 2977.17
   294.6  2981.4   305.9 2980.89   317.2 2977.85   328.6 2978.74   345.6 2985.42
   362.7 2996.69   368.2 2998.26   379.7 2998.36   385.2 2999.74 406.754 3011.57
#Mann= 5 ,-1,0
       0     .06       0      70      .1       0   252.2    .045       0
  276.77      .1       0     350     .06       0
#XS Ineff= 2 , 0
                          298.03         2982.78
Permanent Ineff=
       F       F
Bank Sta=252.2,276.77
XS Rating Curve= 0 ,0
Exp/Cntr(USF)=0,0
Exp/Cntr=0.3,0.1

Type RM Length L Ch R = 1 ,7575    ,225.7,224.7,222.4
XS GIS Cut Line= 3
2313493.19596772495853.6198119372313735.78144047496130.979744006
2313927.90003941496198.161745116
#Sta/Elev= 30
       0  3032.2    41.9  3012.1    53.1 3004.38    68.5 3001.06    83.5 2992.07
   115.2 2977.93     126 2974.31   171.9 2969.13   194.6  2971.8   222.6 2969.93
   245.6 2970.61   249.2 2970.13   254.5 2967.38   259.8    2966   271.9 2966.69
   279.6 2965.21   293.8 2964.07  303.92 2965.21   312.9 2968.72   322.1 2970.34
   336.3 2969.49   377.4 2973.96   395.6 2974.43   415.5 2977.05   440.9 2977.12
   445.9 2977.99     471 2988.91   491.8 2989.33     513 2994.42     572 2999.32
#Mann= 6 ,-1,0
       0     .06       0      60      .1       0   279.6    .045       0
  303.92      .1       0  508.48     .06       0     572      .1       0
Bank Sta=279.6,303.92
XS Rating Curve= 0 ,0
Exp/Cntr=0.3,0.1

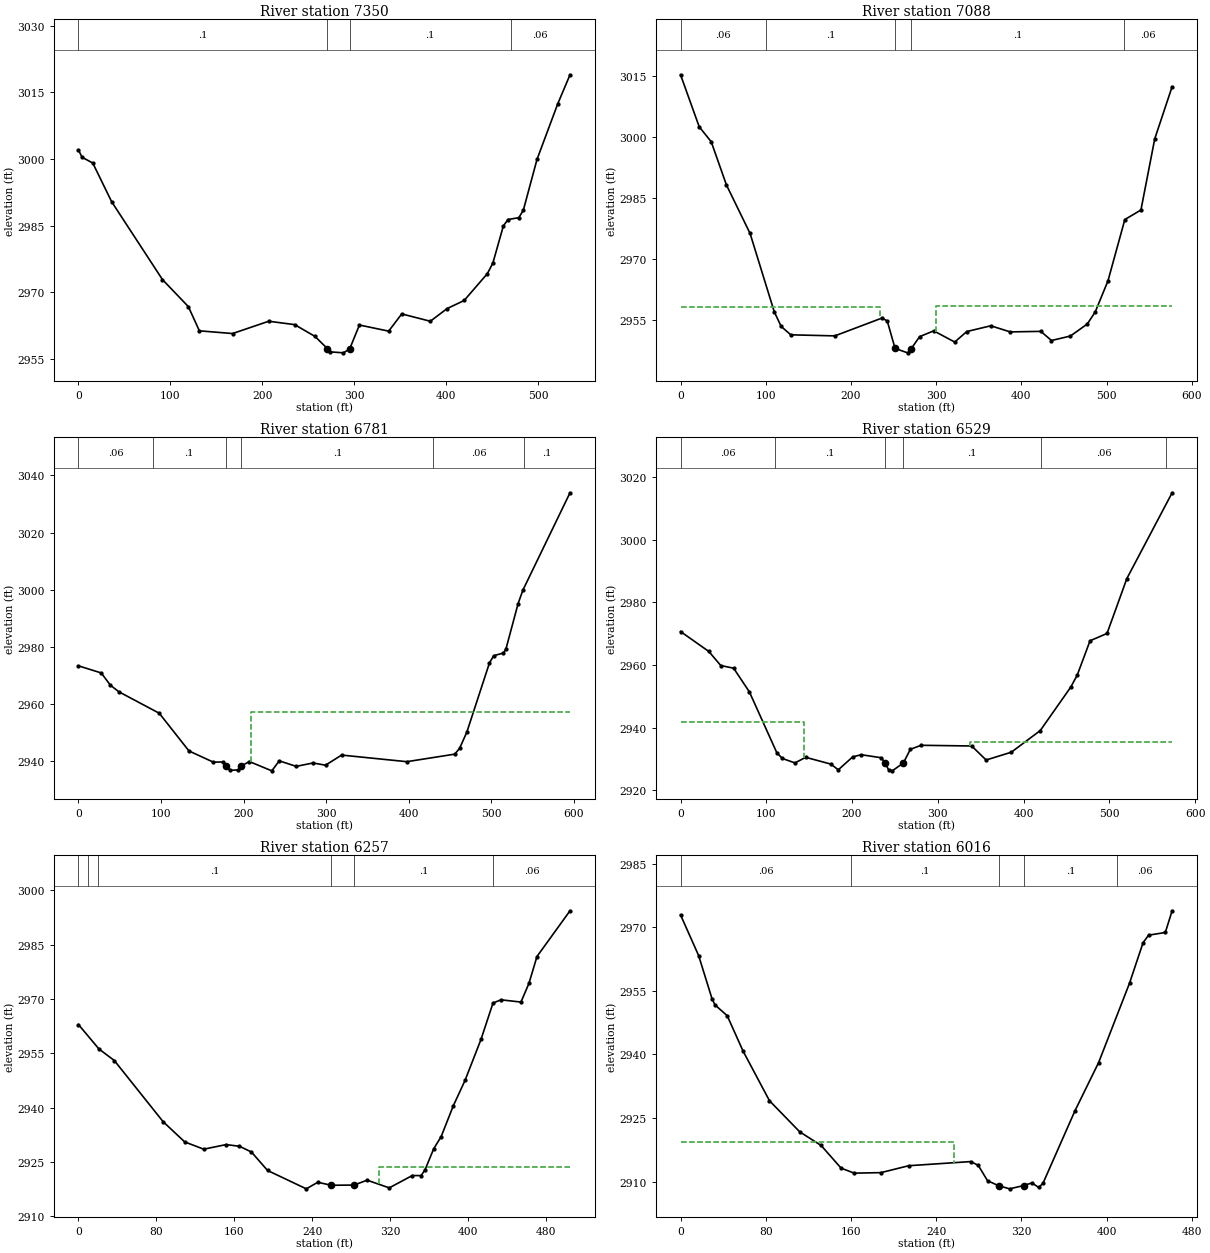
Type RM Length L Ch R = 1 ,7350    ,261.3,262.6,262.7
XS GIS Cut Line= 2
2313350.02170322 496050.424034172313736.91602793496419.164959476
#Sta/Elev= 30
       0 3002.02       4 3000.37    15.6 2999.08    36.1 2990.36    91.4  2972.8
   119.5 2966.72   131.5 2961.26   167.6 2960.65   206.9 2963.42   235.1 2962.66
   257.2    2960   270.7 2957.25   273.7 2956.52   288.1  2956.3   294.9 2957.18
   305.5 2962.57   337.3 2961.19   351.5 2965.07   382.6 2963.42   400.8 2966.27
   419.4  2968.1   444.6 2974.15   450.6 2976.53     462 2984.91   467.1 2986.35
   478.8 2986.76   483.7 2988.44   498.6  2999.9   521.2 3012.46 534.469 3018.97
#Mann= 4 ,-1,0
       0      .1       0   270.7    .045       0   294.9      .1       0
     470     .06       0
Bank Sta=270.7,294.9
XS Rating Curve= 0 ,0
Exp/Cntr(USF)=0,0
Exp/Cntr=0.3,0.1

Type RM Length L Ch R = 1 ,7088    ,311.1,306.9,303.4
XS GIS Cut Line= 2
 2313157.1418346496209.266278917 2313574.6700208496607.506478248
#Sta/Elev= 30
       0 3015.39    21.9 3002.58      36 2998.89    53.9 2988.22    81.6 2976.29
     110 2956.98   118.1 2953.37   129.4  2951.3   181.1 2951.04   236.4 2955.43
   242.6 2954.73  251.81 2947.95   266.5 2946.86   270.9 2947.92   280.6 2950.85
   297.2 2952.28   321.8 2949.52     336 2952.11   364.2 2953.53   386.9 2952.02
   422.9 2952.15   435.4  2949.9   457.6    2951   477.4 2953.96   486.7 2956.91
   501.7  2964.6   521.5 2979.71   540.4 2982.06   556.6  2999.6     577 3012.46
#Mann= 5 ,-1,0
       0     .06       0     100      .1       0  251.81    .045       0
   270.9      .1       0     520     .06       0
#XS Ineff= 2 , 0
          234.59 2958.19  299.83         2958.49
Permanent Ineff=
       F       F
Bank Sta=251.81,270.9
XS Rating Curve= 0 ,0
Exp/Cntr=0.3,0.1

Type RM Length L Ch R = 1 ,6781    ,252.1,251.7,247.6
XS GIS Cut Line= 2
2312961.99279106496509.9319564742313486.17219872496792.444234632
#Sta/Elev= 30
       0 2973.43    27.6 2970.95    38.8 2966.64      49 2964.36    97.9 2956.86
   133.9 2943.68   163.4 2939.77   175.1 2939.83   178.2  2938.4   184.2 2936.91
   193.3 2937.05  197.24 2938.41     207 2939.98   234.2 2936.73   243.3 2940.22
   263.8 2938.29   284.2 2939.48   299.3  2938.7   318.8 2942.24   397.8 2939.93
   455.8 2942.56   461.7 2944.58   470.5 2950.27   497.8 2974.37     503 2976.97
   514.8 2977.92   517.8 2979.26   532.5  2995.1   538.4  2999.9595.4639 3033.92
#Mann= 6 ,-1,0
       0     .06       0      90      .1       0   178.2    .045       0
  197.24      .1       0     430     .06       0     540      .1       0
#XS Ineff= 2 , 0
                           209.3         2957.17
Permanent Ineff=
       F       F
Bank Sta=178.2,197.24
XS Rating Curve= 0 ,0
Exp/Cntr(USF)=0,0
Exp/Cntr=0.3,0.1

Type RM Length L Ch R = 1 ,6529    ,265.3,272.4,278
XS GIS Cut Line= 4
2312842.43033071496713.9346734242312938.16645434 496768.61789792
 2313238.8321319496866.1924196942313341.86862988496970.767026276
#Sta/Elev= 30
       0 2970.71      33 2964.34    46.9 2959.85    61.9    2959    80.3 2951.42
   112.3 2931.97   118.7 2930.16   133.4 2928.74     146 2930.53   175.4 2928.35
   183.9 2926.53   200.7 2930.66   210.7 2931.36   234.3 2930.38   238.5 2928.63
   242.7 2926.53   246.9 2926.21259.78712928.711     268 2933.09   280.5 2934.37
   339.5 2934.15   356.3 2929.67   385.7 2932.16   419.4 2939.06   454.9 2952.91
   462.5 2956.74   477.5 2967.76   497.3 2970.09   520.4 2987.62   573.2 3015.03
#Mann= 6 ,-1,0
       0     .06       0     110      .1       0   238.5    .045       0
259.7871      .1       0  420.25     .06       0  566.35      .1       0
#XS Ineff= 2 , 0
          144.52 2941.71   337.2         2935.27
Permanent Ineff=
       F       F
Bank Sta=238.5,259.7871
XS Rating Curve= 0 ,0
Exp/Cntr=0.3,0.1

Type RM Length L Ch R = 1 ,6257    ,240.5,240.1,240
XS GIS Cut Line= 3
2312730.53694871496857.1157199942312991.49206508497082.898625028
2313025.52968895497238.337107387
#Sta/Elev= 30
       0 2962.94    21.1 2956.17    36.8    2953    86.8 2936.12     109 2930.52
   128.5 2928.51   151.5 2929.78   165.2 2929.31   177.4 2927.74     194 2922.63
   233.7 2917.56   245.5 2919.37   259.3 2918.55  282.61  2918.6   296.1 2919.95
   318.8 2917.83   342.4 2921.23   351.5 2921.22   355.6 2922.88   364.4 2928.63
     372 2931.96   384.5  2940.5   396.5 2947.49   412.9 2958.83   425.2 2968.87
   433.4 2969.76   453.9 2969.14   462.1 2974.32   470.3 2981.72504.1948 2994.35
#Mann= 6 ,-1,0
       0      .1       0      10     .06       0      20      .1       0
   259.3    .045       0  282.61      .1       0  425.07     .06       0
#XS Ineff= 2 , 0
                          308.14         2923.48
Permanent Ineff=
       F       F
Bank Sta=259.3,282.61
XS Rating Curve= 0 ,0
Exp/Cntr(USF)=0,0
Exp/Cntr=0.3,0.1

Type RM Length L Ch R = 1 ,6016    ,275.8,275.5,273.4
XS GIS Cut Line= 2
2312531.15973311497004.5013731242312885.10269557497300.654844216
#Sta/Elev= 30
       0  2972.9      17  2963.3    29.6 2953.09    32.4 2951.67    43.8 2949.13
    58.7 2940.79    83.5 2929.08   111.9 2921.75     132 2918.53   150.7  2913.2
     163 2912.01   188.1 2912.13   214.2 2913.76   272.5 2914.74   279.5 2913.85
   288.2 2910.23   298.6 2909.04     309 2908.31   322.1 2909.09   322.1  2909.1
   329.9  2909.7   336.3 2908.63   340.3 2909.64   370.3 2926.72   392.5 2938.08
   421.5 2956.79   434.2 2966.33   439.4 2968.12   455.1 2968.75   461.5 2973.87
#Mann= 5 ,-1,0
       0     .06       0     160      .1       0   298.6    .045       0
   322.1      .1       0     410     .06       0
#XS Ineff= 2 , 0
           256.9  2919.3
Permanent Ineff=
       F       F
Bank Sta=298.6,322.1
XS Rating Curve= 0 ,0
Exp/Cntr=0.3,0.1

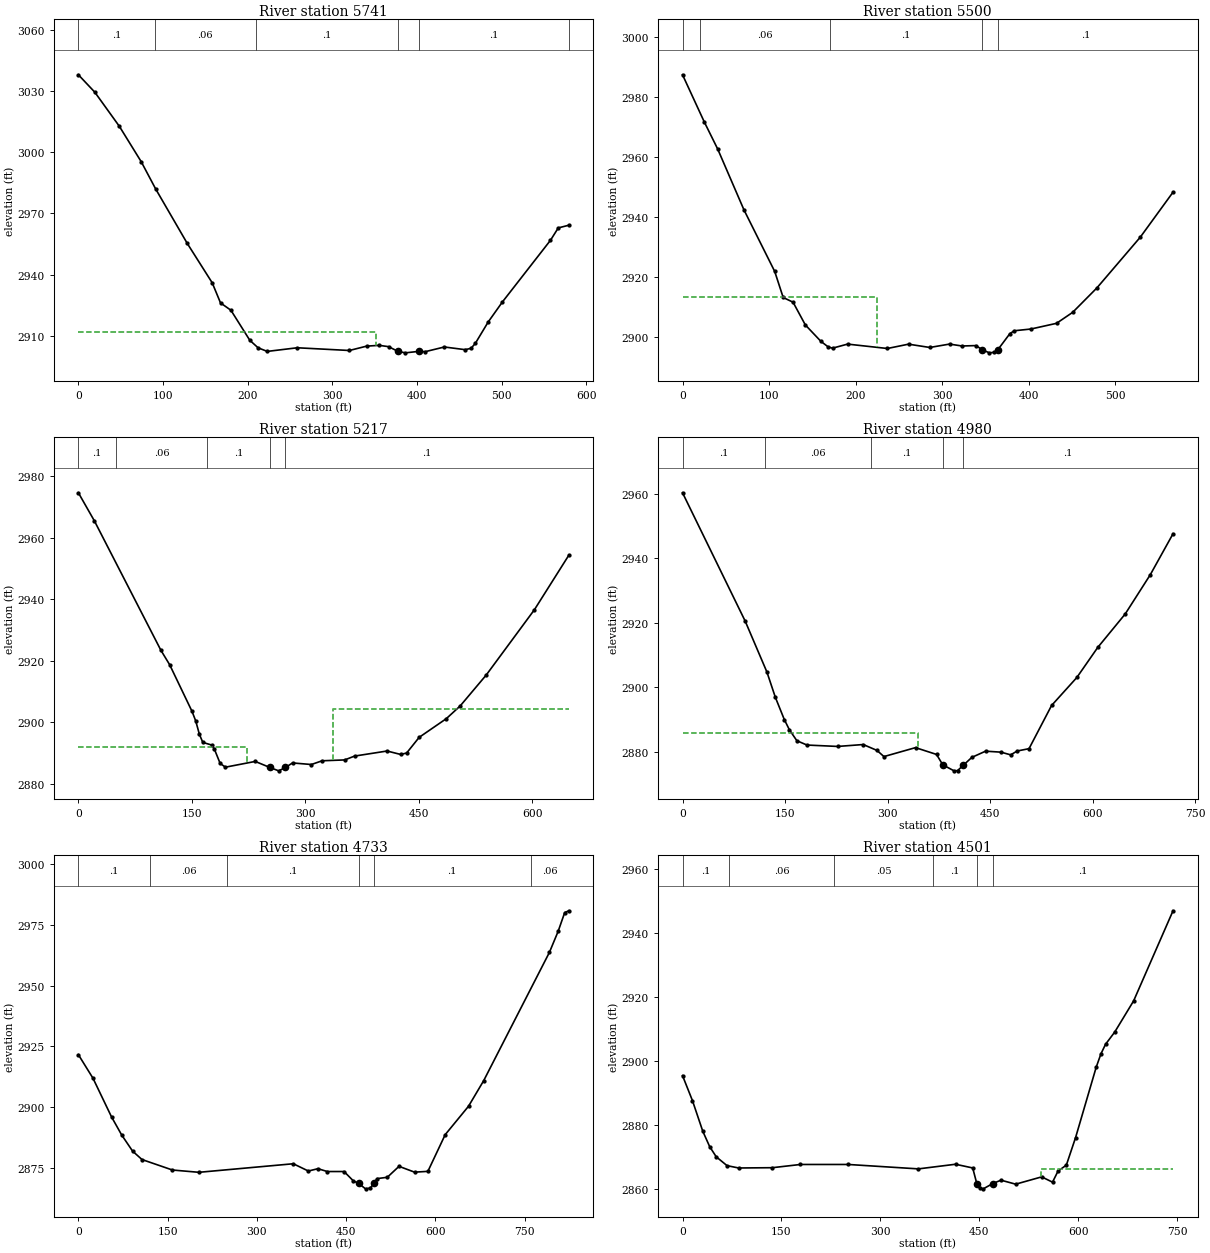
Type RM Length L Ch R = 1 ,5741    ,235.6,241,244.1
XS GIS Cut Line= 2
 2312280.0061671497181.8287467192312749.80706686 497520.94559338
#Sta/Elev= 30
       0 3037.85    19.4 3029.33    48.4 3012.63    74.2 2995.33    91.3 2981.97
   128.6 2955.33   158.1 2936.04   167.9 2926.21   180.2 2922.61   202.5 2907.92
   212.3 2904.23   223.1 2902.47   258.6 2904.25   320.1 2902.92   340.6 2905.06
   355.4 2905.43   366.4  2904.8   377.8 2902.43   386.4 2901.77   402.1 2902.49
   409.7 2902.34   432.3 2904.63   456.8 2903.33   463.8 2903.97   468.9  2906.4
   484.1 2916.87     501 2926.73   557.7 2956.87   566.9 2962.92579.4075 2964.23
#Mann= 6 ,-1,0
       0      .1       0      90     .06       0     210      .1       0
   377.8    .045       0   402.1      .1       0  579.41     .06       0
#XS Ineff= 2 , 0
          351.55 2911.78
Permanent Ineff=
       F       F
Bank Sta=377.8,402.1
XS Rating Curve= 0 ,0
Exp/Cntr(USF)=0,0
Exp/Cntr=0.3,0.1

Type RM Length L Ch R = 1 ,5500    ,287,283.1,276.1
XS GIS Cut Line= 4
2312244.06785561497346.0975092492312362.71759311497438.234167365
2312528.14044514497675.615960028 2312619.2983747497764.238406621
#Sta/Elev= 30
       0 2987.31    25.1 2971.61    40.7 2962.51      71 2942.26   106.5 2921.75
   116.3 2913.06   127.7 2911.49   141.9 2903.91   159.8 2898.46   168.4 2896.56
   173.3 2896.17   190.7 2897.52   236.7 2896.06   261.1  2897.5   285.7  2896.4
   308.5 2897.53   322.9 2896.89   339.1 2897.03   345.9 2895.69   354.5 2894.61
   360.3 2894.79  364.37 2895.68   378.1 2900.97   383.2 2901.97   402.5 2902.55
   432.1 2904.45   450.8 2908.12   478.7 2916.24   528.9 2933.18   566.7 2948.17
#Mann= 5 ,-1,0
       0      .1       0      20     .06       0  170.22      .1       0
   345.9    .045       0  364.37      .1       0
#XS Ineff= 2 , 0
          224.25 2913.07
Permanent Ineff=
       F       F
Bank Sta=345.9,364.37
XS Rating Curve= 0 ,0
Exp/Cntr=0.3,0.1

Type RM Length L Ch R = 1 ,5217    ,234.9,237.1,240
XS GIS Cut Line= 2
2312018.23161244497537.5435994342312544.90431107497915.739420262
#Sta/Elev= 30
       0 2974.63    21.2 2965.47   109.1 2923.38   120.6 2918.72   150.2 2903.53
   155.1 2900.42     160 2896.03   164.5 2893.42     176 2892.58   179.7 2891.28
   187.4 2886.59   194.4 2885.36   233.8 2887.23   253.1 2885.27   264.8 2884.17
   273.7 2885.26   283.1 2886.74     308 2886.23   322.2 2887.44     352 2887.72
   365.1 2888.97   408.1 2890.62   425.9 2889.51   433.9 2889.96   450.5 2895.07
   486.3 2901.13   504.7 2905.28   539.2 2915.36   602.9 2936.61648.3951 2954.34
#Mann= 5 ,-1,0
       0      .1       0      50     .06       0     170      .1       0
   253.1    .045       0   273.7      .1       0
#XS Ineff= 2 , 0
          222.42 2891.93  337.21         2904.15
Permanent Ineff=
       F       F
Bank Sta=253.1,273.7
XS Rating Curve= 0 ,0
Exp/Cntr(USF)=0,0
Exp/Cntr=0.3,0.1

Type RM Length L Ch R = 1 ,4980    ,245.1,246.7,243.7
XS GIS Cut Line= 3
2311882.56417466497619.5392642452312049.76325375 497826.44881372
2312402.16286957498108.994274738
#Sta/Elev= 30
       0 2960.24    91.7 2920.47   123.5 2904.69   135.8 2896.89   148.9 2889.99
   156.4  2886.8   167.3 2883.42   182.1 2882.08     227 2881.65   264.4 2882.24
   284.5 2880.42   294.7 2878.51   340.9 2881.28   371.7 2879.17  380.75 2875.96
   397.3 2874.09   402.4 2874.16   411.1 2875.87   423.3 2878.26   443.4 2880.18
     466 2879.88   480.2 2879.04   489.6 2880.23     507 2880.96     540 2894.34
     577 2903.02   607.5 2912.31   647.7 2922.68   684.4 2934.84   717.7 2947.54
#Mann= 5 ,-1,0
       0      .1       0     120     .06       0  276.02      .1       0
  380.75    .045       0   411.1      .1       0
#XS Ineff= 2 , 0
          344.79 2885.78
Permanent Ineff=
       F       F
Bank Sta=380.75,411.1
XS Rating Curve= 0 ,0
Exp/Cntr=0.3,0.1

Type RM Length L Ch R = 1 ,4733    ,231.3,232.1,231.6
XS GIS Cut Line= 2
2311669.45102212497813.486476112  2312309.582467498333.155548434
#Sta/Elev= 30
       0 2921.59    24.5 2911.91    55.7 2895.98    72.8 2888.51    91.1 2881.88
   106.9 2878.41   158.1 2874.09   202.6 2873.15   361.3 2876.67   386.6 2873.67
   402.7 2874.64   418.4 2873.47   446.6 2873.47   462.1 2869.64   470.9  2868.6
   482.7 2866.34   490.8 2866.66  496.88 2868.66   502.2 2870.55   519.3  2871.1
     539 2875.61   565.1 2873.21   587.5 2873.54   616.6 2888.65   655.8 2900.35
   681.3 2910.89   791.8 2963.73   806.5 2972.41   817.5 2980.12   824.5 2980.85
#Mann= 6 ,-1,0
       0      .1       0     120     .06       0     250      .1       0
   470.9    .045       0  496.88      .1       0     760     .06       0
Bank Sta=470.9,496.88
XS Rating Curve= 0 ,0
Exp/Cntr(USF)=0,0
Exp/Cntr=0.3,0.1

Type RM Length L Ch R = 1 ,4501    ,276.2,275.7,275
XS GIS Cut Line= 2
     2311564.754      498000.5972312131.44782534498482.081803227
#Sta/Elev= 30
       0 2895.41      15 2887.61    30.7    2878    41.2 2873.16    51.1 2869.99
    67.5 2867.22    85.1 2866.49   136.2 2866.58   178.8 2867.59   251.2 2867.59
   357.6 2866.21   413.9 2867.66   439.9  2866.5446.19212861.556   450.6 2860.11
   455.9 2859.96   470.4 2861.62   482.8 2862.67   505.1 2861.42   544.5 2863.71
   560.9 2862.05   569.2 2865.49   581.9  2867.4   595.9 2876.03   627.1 2898.02
   634.3 2902.22   641.3 2905.23   655.3 2909.08   683.9 2918.83   743.6 2947.03
#Mann= 6 ,-1,0
       0      .1       0      70     .06       0     230     .05       0
     380      .1       0446.1921    .045       0   470.4      .1       0
#XS Ineff= 2 , 0
                          543.89         2866.06
Permanent Ineff=
       F       F
Bank Sta=446.1921,470.4
XS Rating Curve= 0 ,0
Exp/Cntr=0.3,0.1

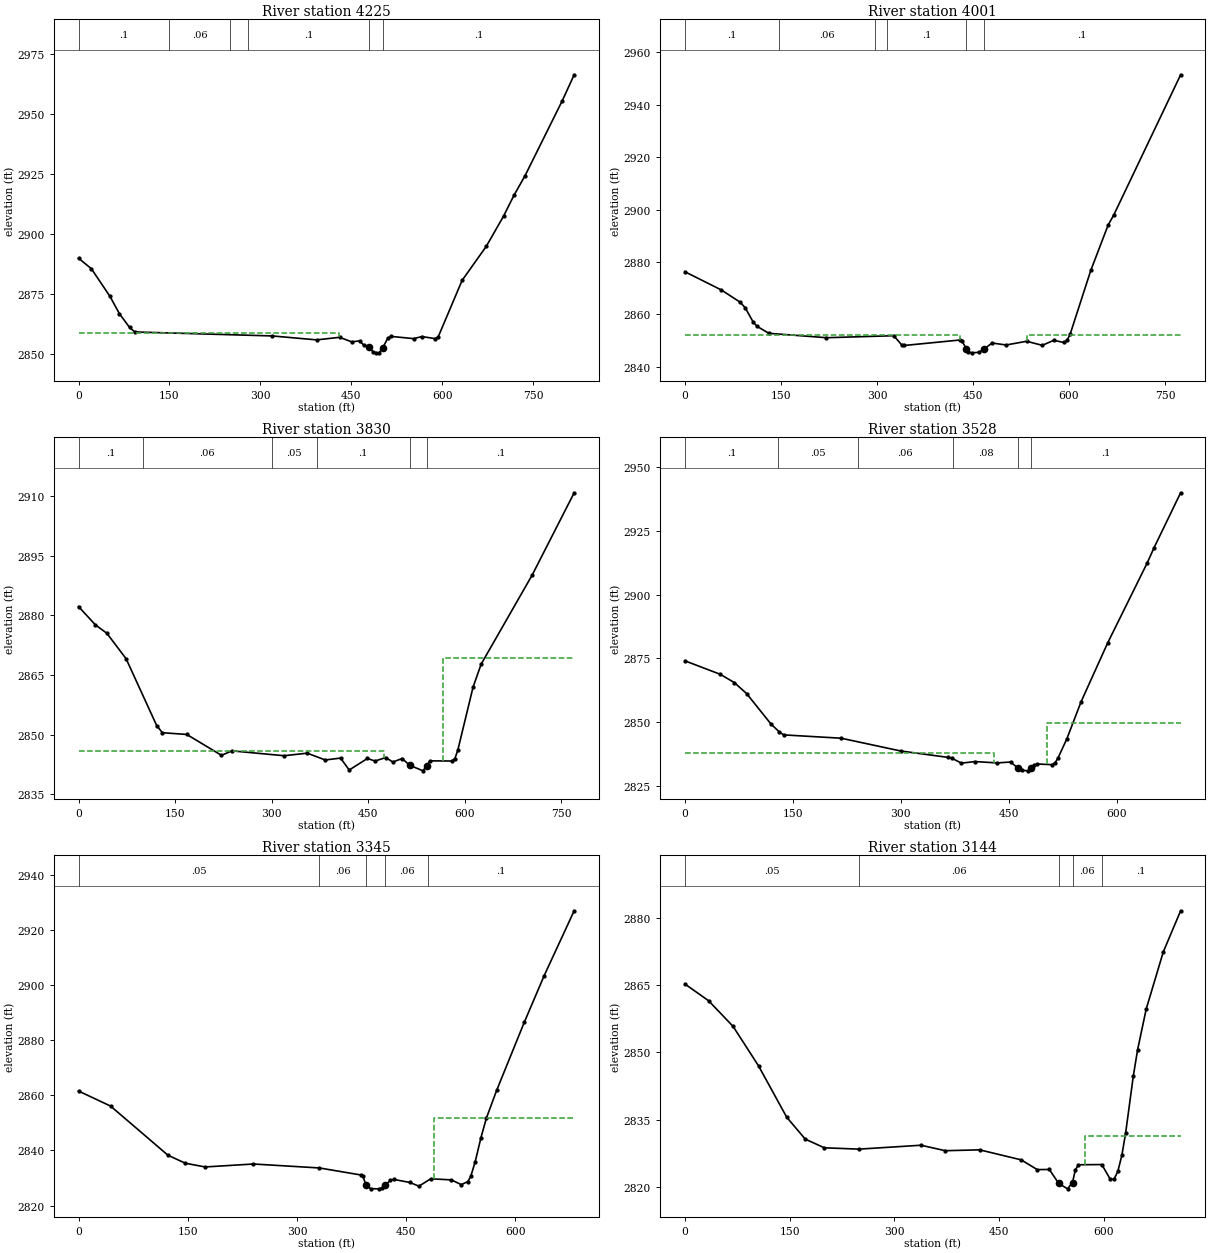
Type RM Length L Ch R = 1 ,4225    ,222.6,224.1,223.5
XS GIS Cut Line= 2
2311351.48638757498188.8808464152311991.61783246498697.344116638
#Sta/Elev= 30
       0    2890    21.3 2885.59      52 2874.06    67.3 2866.96    84.1 2861.22
    92.8 2859.31   319.6 2857.65   392.8 2856.01   430.6 2857.08   450.5 2855.19
   463.5 2855.58   470.8 2853.78     479 2852.88   486.2 2850.97   491.3 2850.62
   496.1 2850.68   501.8 2852.76   510.3 2856.78     516 2857.45   552.6 2856.53
   566.4 2857.39   588.3 2856.53   592.9 2857.05   632.7 2880.77   672.6 2894.94
   701.1 2907.52   718.1 2916.09   736.5 2924.33   797.8 2955.46817.4981 2966.29
#Mann= 6 ,-1,0
       0      .1       0     150     .06       0     250     .05       0
     280      .1       0     479    .045       0   501.8      .1       0
#XS Ineff= 2 , 0
          430.04  2858.8
Permanent Ineff=
       F       F
Bank Sta=479,501.8
XS Rating Curve= 0 ,0
Exp/Cntr(USF)=0,0
Exp/Cntr=0.3,0.1

Type RM Length L Ch R = 1 ,4001    ,168.7,171,169.3
XS GIS Cut Line= 3
2311282.54355997498314.2830442292311309.46462971498417.199064173
2311814.25037482498854.684637933
#Sta/Elev= 30
       0 2876.24    56.7 2869.31    85.8 2864.69      94 2862.55   106.4 2857.11
   112.5 2855.42   131.1 2852.74   221.1 2851.06   326.2 2851.82   338.4 2848.37
   342.9  2848.1     430 2850.19   432.9 2849.76439.79062846.739   442.9  2845.6
   448.6 2845.28   459.9  2845.5   466.7 2846.62   479.8 2849.04   501.7 2848.28
   533.9  2849.7   558.3 2848.14   576.2 2850.07   591.6 2849.24   596.9    2850
   601.7 2852.34     634 2876.74   661.2 2894.13   669.7 2897.81   774.4 2951.49
#Mann= 6 ,-1,0
       0      .1       0  146.38     .06       0  296.38     .05       0
  316.38      .1       0439.7906    .045       0   466.7      .1       0
#XS Ineff= 2 , 0
          429.46 2852.01  534.04         2851.94
Permanent Ineff=
       F       F
Bank Sta=439.7906,466.7
XS Rating Curve= 0 ,0
Exp/Cntr=0.3,0.1

Type RM Length L Ch R = 1 ,3830    ,291.7,301.9,311
XS GIS Cut Line= 3
2311099.61004605498435.5260843342311545.76698146498840.180049005
2311706.59099306 498888.60018153
#Sta/Elev= 30
       0 2882.22    26.3 2877.61      44 2875.51    73.9 2869.12   121.5  2852.3
   130.4  2850.5   168.2 2850.07   222.2 2844.82   238.4 2845.94   319.4 2844.72
   355.5 2845.36   383.5 2843.65   407.3 2844.13   420.7 2841.13     449 2844.03
   460.9 2843.38   477.3 2844.26   488.6 2843.14     503 2844.02   514.5 2842.33
   535.4 2840.92   540.8 2842.21   546.2 2843.43     580 2843.39   584.9    2844
   589.4 2846.09   613.2 2861.98   625.7 2867.73   705.1 2890.16770.2845 2910.82
#Mann= 6 ,-1,0
       0      .1       0     100     .06       0     300     .05       0
     370      .1       0   514.5    .045       0   540.8      .1       0
#XS Ineff= 2 , 0
          474.14 2846.03  566.11         2869.27
Permanent Ineff=
       F       F
Bank Sta=514.5,540.8
XS Rating Curve= 0 ,0
Exp/Cntr(USF)=0,0
Exp/Cntr=0.3,0.1

Type RM Length L Ch R = 1 ,3528    ,193,183,171.7
XS GIS Cut Line= 4
2311000.21561901498548.2118377522311186.07456842498719.129717693
2311256.24047651 498997.847712132311366.91985046499097.905558157
#Sta/Elev= 30
       0 2874.05    48.9  2868.8    68.6 2865.55    85.6 2861.27   119.5 2849.36
   131.4 2846.15   137.3 2845.08   217.3 2843.77     300 2838.77     366 2836.27
   371.3  2835.9   384.4 2834.02   403.1 2834.64   433.9 2834.11   452.6 2834.46
   463.5 2831.98   469.1 2831.22   476.7 2831.01   481.5 2831.99   485.6 2833.22
   489.7 2833.69   510.4 2833.42   514.5 2834.13   518.6 2836.02     531  2843.6
   550.8 2858.11   587.5 2880.97   642.3 2912.18   652.2 2918.35   689.1 2939.82
#Mann= 6 ,-1,0
       0      .1       0     130     .05       0     240     .06       0
   372.5     .08       0   463.5    .045       0   481.5      .1       0
#XS Ineff= 2 , 0
          430.09 2837.99  503.49         2849.85
Permanent Ineff=
       F       F
Bank Sta=463.5,481.5
XS Rating Curve= 0 ,0
Exp/Cntr=0.3,0.1

Type RM Length L Ch R = 1 ,3345    ,201.1,201.5,201.3
XS GIS Cut Line= 2
2310767.58628017498710.4832654572311270.80980034499168.745233995
#Sta/Elev= 30
       0 2861.54    44.1 2856.07   122.8 2838.27   146.7 2835.37   173.9 2834.02
   240.2 2835.09   330.8 2833.66   387.4 2831.13   390.2 2830.79  394.88 2827.49
   401.1 2826.15     412 2826.09   417.4 2826.38   421.4 2827.46   428.2 2829.16
   432.7 2829.52   455.2 2828.39   467.4 2827.05   483.7 2829.74     512 2829.33
   525.6 2827.61   534.7 2828.73   538.7 2830.69   544.6  2835.8   552.6 2844.63
   560.1 2851.73   574.3 2861.86   612.1 2886.44   639.4 2903.34680.6158 2926.86
#Mann= 5 ,-1,0
       0     .05       0     330     .06       0  394.88    .045       0
   421.4     .06       0     480      .1       0
#XS Ineff= 2 , 0
                          488.37          2851.9
Permanent Ineff=
       F       F
Bank Sta=394.88,421.4
XS Rating Curve= 0 ,0
Exp/Cntr(USF)=0,0
Exp/Cntr=0.3,0.1

Type RM Length L Ch R = 1 ,3144    ,164.7,173,181
XS GIS Cut Line= 3
2310672.28834521498720.1987545672310889.16453338499076.148014079
2311101.17802675499279.408656806
#Sta/Elev= 30
       0 2865.26    33.9 2861.53      69  2855.8   105.4 2847.01   145.8 2835.55
   172.4 2830.66   199.7 2828.72   249.4 2828.42   338.3 2829.29   373.2 2828.07
   422.5 2828.26   481.9 2826.03     505 2823.85   522.3 2823.88   535.7 2820.78
   548.4 2819.56   555.5 2820.96   559.5 2823.75     564 2824.93   597.5 2824.98
   609.4 2821.76   614.9 2821.66   620.5 2823.48   626.2    2827   631.6 2831.94
   642.6 2844.66   648.8 2850.59   661.1 2859.65   685.6 2872.42   710.5 2881.61
#Mann= 5 ,-1,0
       0     .05       0   249.4     .06       0   535.7    .045       0
   555.5     .06       0   597.5      .1       0
#XS Ineff= 2 , 0
                          572.76         2831.46
Permanent Ineff=
       F       F
Bank Sta=535.7,555.5
XS Rating Curve= 0 ,0
Exp/Cntr(USF)=0,0
Exp/Cntr=0.3,0.1