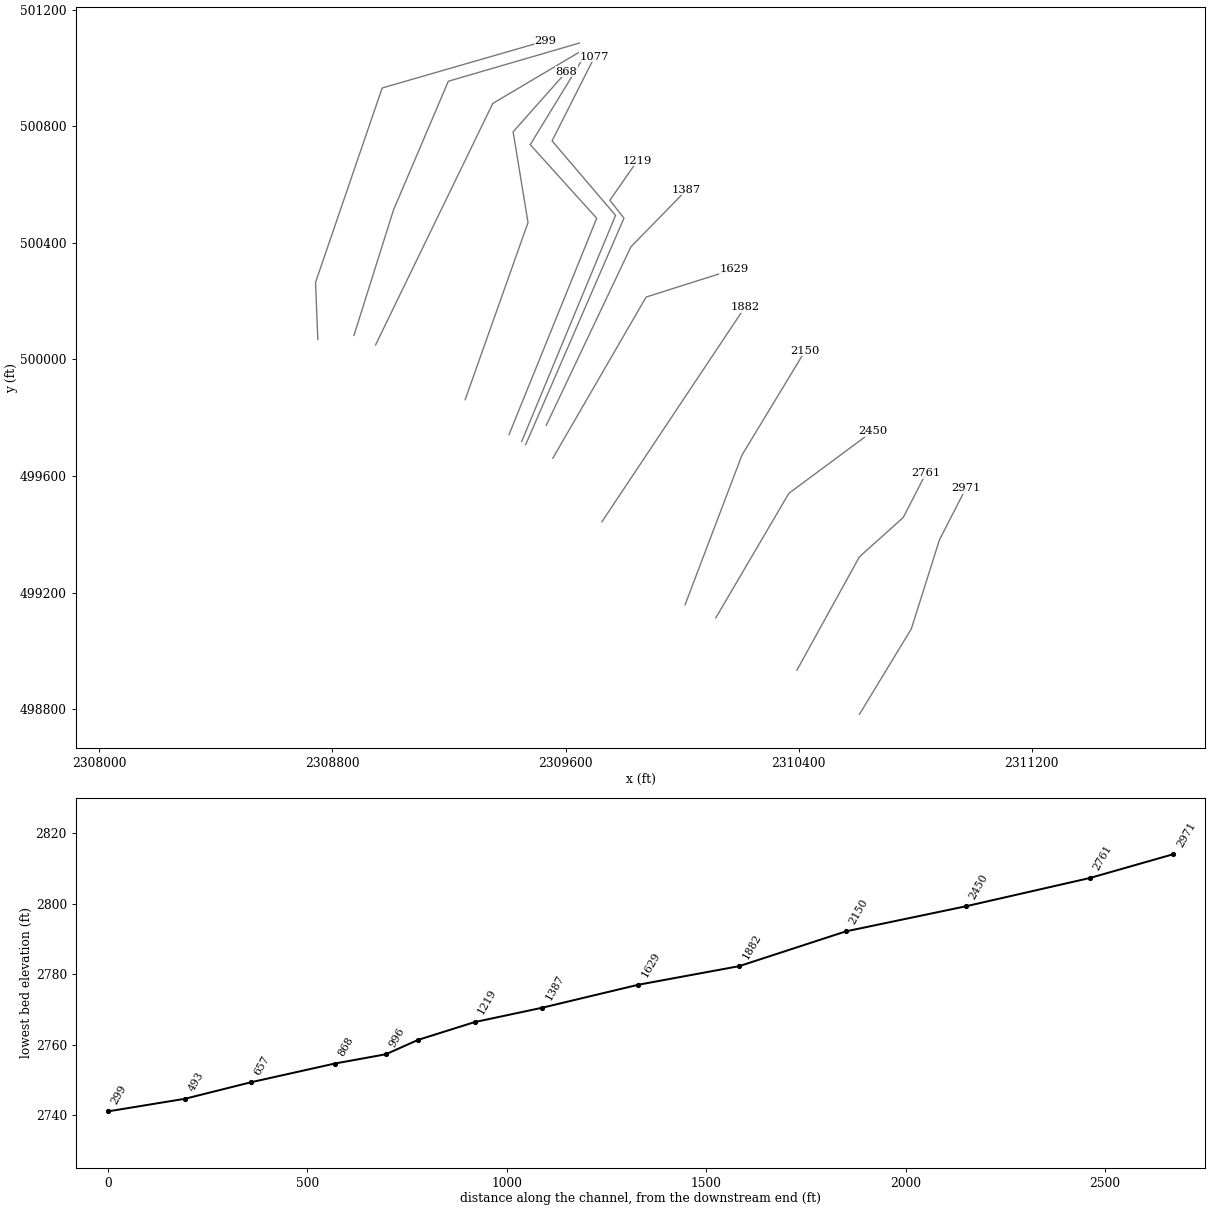
HEC-RAS study STONYRB.prj: STONYRB

--- STONYRB.g01 (geometry) --- (continued)

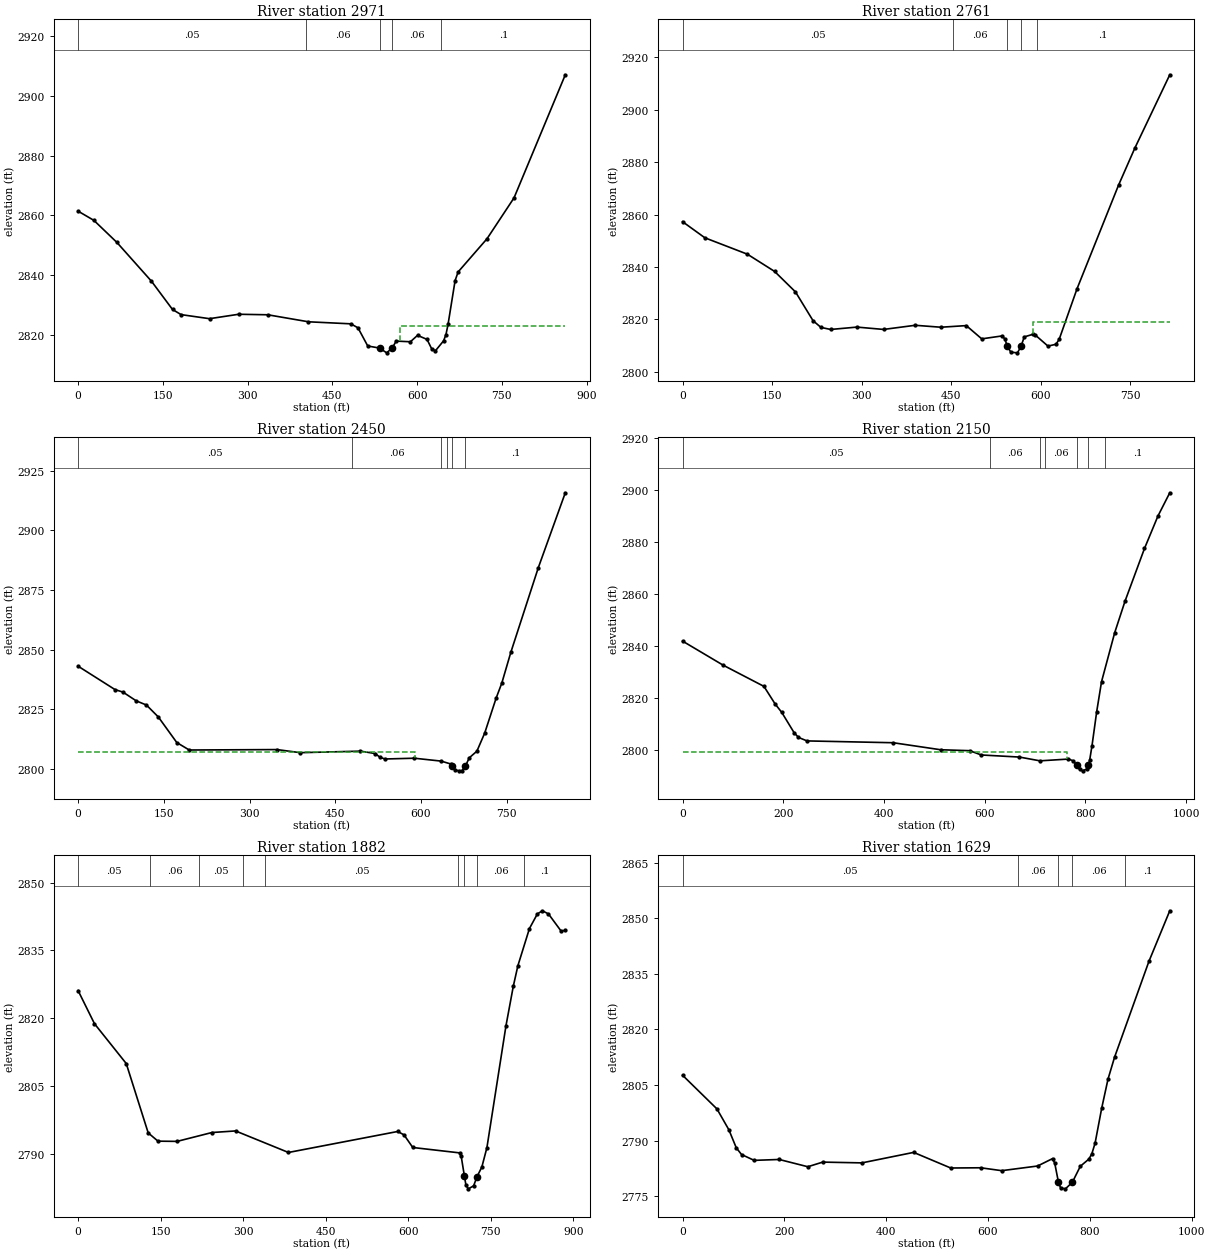
Type RM Length L Ch R = 1 ,2971    ,217.8,209.5,200.5
XS GIS Cut Line= 4
2310608.55090447 498782.365734952310786.60847509 499075.36354984
2310883.44874014499381.4479590152310974.02366869 499557.83373495
#Sta/Elev= 30
       0 2861.45      28 2858.36    68.6    2851   129.9 2837.99   167.1 2828.54
   182.3 2826.82   232.6 2825.46   284.2 2826.94   335.6 2826.77   407.7 2824.42
   482.6 2823.74   495.3 2822.41   512.6 2816.32   533.5 2815.63   546.1 2814.03
   555.9 2815.65   562.9 2817.96   588.1 2817.74   600.7 2819.88   617.5 2818.53
     626 2815.28   632.4 2814.72   646.8 2818.05     651 2820.12   654.7 2823.53
   667.2 2838.22   672.6 2841.12   723.7 2852.22   771.5  2865.9   862.2 2907.09
#Mann= 5 ,-1,0
       0     .05       0  402.86     .06       0   533.5    .045       0
   555.9     .06       0  642.86      .1       0
#XS Ineff= 2 , 0
                          569.35         2822.85
Permanent Ineff=
       F       F
Bank Sta=533.5,555.9
XS Rating Curve= 0 ,0
Exp/Cntr=0.3,0.1

Type RM Length L Ch R = 1 ,2761    ,312.3,311.1,309.2
XS GIS Cut Line= 4
2310394.09746384498934.0927818792310608.49155901499322.652083806
2310758.93982793499457.5367386962310837.11373882499609.480043062
#Sta/Elev= 30
       0 2857.26    37.4 2851.12   108.6 2844.88   154.3  2838.3   189.3 2830.49
   218.7 2819.54   231.9 2816.98   248.2 2816.19   292.3 2817.09     337  2816.2
   389.9 2817.78     433 2817.04   475.6 2817.66   501.5 2812.61     536 2813.74
   540.1 2812.56   544.5 2809.84   550.2 2807.53   561.4 2807.28   567.4 2809.79
   572.8 2813.36     587 2814.32   591.4 2814.04   612.5 2809.85     626 2810.54
   631.4 2812.49   661.3 2831.74   730.9 2871.23   757.9 2885.19   816.7 2913.25
#Mann= 5 ,-1,0
       0     .05       0  453.78     .06       0   544.5    .045       0
   567.4     .06       0  593.78      .1       0
#XS Ineff= 2 , 0
                          586.79         2818.86
Permanent Ineff=
       F       F
Bank Sta=544.5,567.4
XS Rating Curve= 0 ,0
Exp/Cntr=0.3,0.1

Type RM Length L Ch R = 1 ,2450    ,293.4,300.5,306.2
XS GIS Cut Line= 3
2310115.64378153499113.4079396812310366.39089639499540.542680167
2310653.45311064499753.245405187
#Sta/Elev= 30
       0 2843.12    64.7  2833.3    78.6 2832.25   101.8 2828.58   119.6 2826.84
   140.5 2821.81   172.7 2811.12   194.5 2807.99     348 2808.17   388.9 2806.87
   494.1 2807.51   519.9 2806.52   528.5 2804.89   537.3 2804.23   588.5 2804.55
   635.3 2803.34   651.8 2802.16   654.6 2801.23     660 2799.58   666.8 2799.26
   671.8 2799.34   677.8 2801.25   684.5 2804.71   697.9  2807.5   711.6 2815.12
   731.5  2829.7   741.5 2836.04   757.2 2848.88   805.4 2884.43852.5735 2915.79
#Mann= 6 ,-1,0
       0     .05       0     480     .06       0   635.3     .07       0
   645.3      .1       0   654.6    .045       0   677.8      .1       0
#XS Ineff= 2 , 0
           589.6 2807.28
Permanent Ineff=
       F       F
Bank Sta=654.6,677.8
XS Rating Curve= 0 ,0
Exp/Cntr(USF)=0,0
Exp/Cntr=0.3,0.1

Type RM Length L Ch R = 1 ,2150    ,266.5,267.7,265.5
XS GIS Cut Line= 3
2310010.14909939499158.1810021982310205.56688479499671.968754163
2310422.21622032500029.257204851
#Sta/Elev= 30
       0 2841.97    80.2 2832.77   161.6 2824.59   183.7 2817.86     197 2814.59
   221.5  2806.8   230.2 2804.99   247.1 2803.65   418.3 2802.95   512.4 2800.26
   570.2  2799.9   593.2 2798.25     669 2797.45   709.7    2796   766.3 2796.68
   775.7 2796.01   782.5 2794.36   788.4 2792.68   794.2 2792.16   803.7 2792.95
   805.8 2794.26   808.4 2796.23   813.1 2801.86   822.4 2814.92     832  2826.4
   858.2 2845.25   878.7 2857.34   917.3 2877.55   944.1 2890.03   967.5 2898.92
#Mann= 7 ,-1,0
       0     .05       0   609.7     .06       0   709.7     .08       0
   719.7     .06       0   782.5    .045       0   805.8     .06       0
   839.7      .1       0
#XS Ineff= 2 , 0
          763.96 2799.46
Permanent Ineff=
       F       F
Bank Sta=782.5,805.8
XS Rating Curve= 0 ,0
Exp/Cntr=0.3,0.1

Type RM Length L Ch R = 1 ,1882    ,266.3,253.3,243
XS GIS Cut Line= 2
2309724.88653605499443.1698279872310215.91962603500179.719462954
#Sta/Elev= 30
       0 2826.13    29.8  2818.8    87.5    2810   127.4 2794.66   145.2 2792.84
   179.8 2792.79   243.2 2794.75   286.1  2795.1   382.2 2790.34   580.7 2794.98
   592.2 2794.23   608.1 2791.44   693.2 2790.25   696.1 2789.49   701.9 2785.13
   704.7 2783.11   709.1  2782.3   718.7 2782.97   724.9 2785.01   733.6 2787.12
   742.8  2791.4   777.5 2818.39   790.8 2827.11   799.1 2831.63   820.1 2839.85
   834.5 2843.08   843.7 2843.77   854.7 2843.07   877.4 2839.32885.2225 2839.42
#Mann= 9 ,-1,0
       0     .05       0     130     .06       0     220     .05       0
     300     .06       0     340     .05       0     690     .06       0
   701.9    .045       0   724.9     .06       0     810      .1       0
Bank Sta=701.9,724.9
XS Rating Curve= 0 ,0
Exp/Cntr(USF)=0,0
Exp/Cntr=0.3,0.1

Type RM Length L Ch R = 1 ,1629    ,231.6,241.7,249.8
XS GIS Cut Line= 3
2309556.22734428 499660.93232876  2309876.466316500213.878286605
 2310179.6258759500309.949978123
#Sta/Elev= 30
       0 2807.65    67.5 2798.58    90.9 2792.96   105.5 2788.08   115.8 2786.28
   140.6  2784.7   189.8 2784.94     246 2782.98   275.3 2784.23   352.3 2784.02
   453.9 2786.85   526.7 2782.64   585.6  2782.7   626.9 2781.92   697.4 2783.18
   726.8 2785.18     731 2783.96  738.37 2778.79   742.6 2777.25     752 2777.02
   765.6 2778.78   781.3 2783.11   798.1 2785.04   803.9 2786.46   810.3 2789.35
   823.3 2798.78   835.7 2806.62   848.5  2812.5     916 2838.35957.0034 2852.01
#Mann= 5 ,-1,0
       0     .05       0  658.99     .06       0  738.37    .045       0
   765.6     .06       0  868.99      .1       0
Bank Sta=738.37,765.6
XS Rating Curve= 0 ,0
Exp/Cntr(USF)=0,0
Exp/Cntr=0.3,0.1

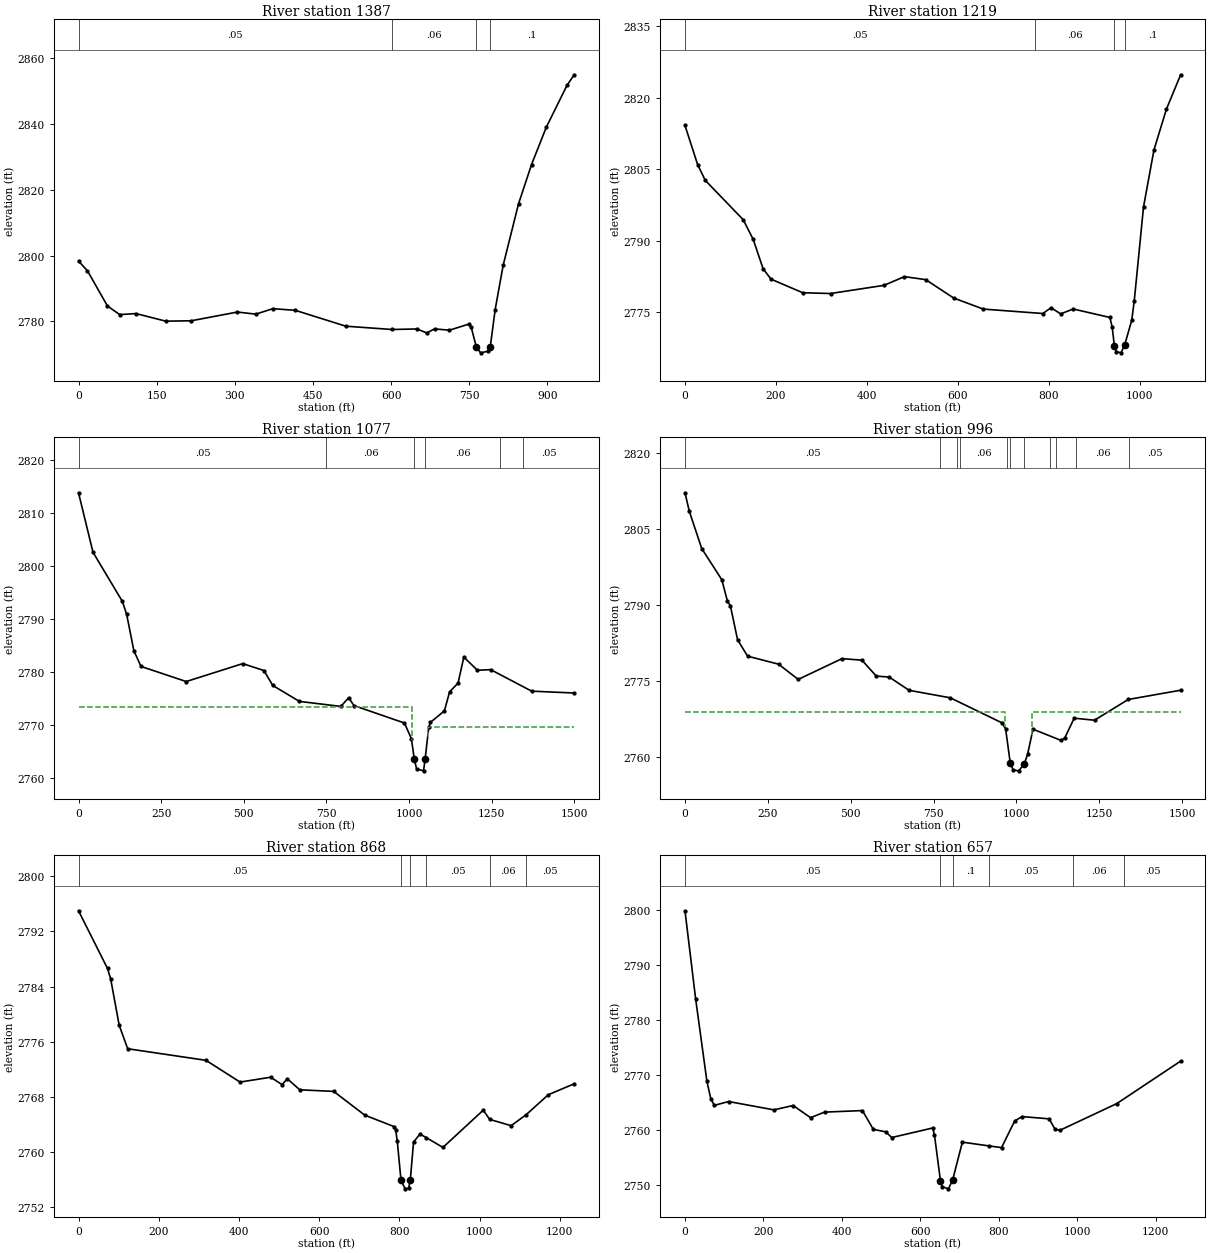
Type RM Length L Ch R = 1 ,1387    ,165.8,168.5,171.6
XS GIS Cut Line= 3
 2309533.6691079499773.7273649442309824.20048458500385.918480102
2310015.41756414500581.582468482
#Sta/Elev= 30
       0 2798.32    17.1 2795.38    55.5 2784.71    79.1 2782.08   110.1  2782.4
   167.6 2780.09   216.3 2780.21   304.9 2782.86   340.3 2782.22   372.8 2783.88
   415.8 2783.39     513 2778.57   601.5 2777.57   649.6 2777.73   668.2 2776.53
   683.3 2777.75   711.9 2777.36   749.3 2779.22   753.5 2778.34   763.4 2772.25
   771.7 2770.49   786.3    2771   790.2 2772.32   799.6  2783.6   814.9    2797
   844.4 2815.67   869.4 2827.58   897.7 2838.89   937.3 2851.55   951.2  2854.8
#Mann= 4 ,-1,0
       0     .05       0   601.5     .06       0   763.4    .045       0
   790.2      .1       0
Bank Sta=763.4,790.2
XS Rating Curve= 0 ,0
Exp/Cntr(USF)=0,0
Exp/Cntr=0.3,0.1

Type RM Length L Ch R = 1 ,1219    ,122.9,141.5,173
BEGIN DESCRIPTION:
structure xs 4
END DESCRIPTION:
XS GIS Cut Line= 4
2309463.12859893499707.6610265332309800.48919392500484.474191962
2309752.11569228500545.7115970152309846.01247164500680.844416298
#Sta/Elev= 30
       0  2814.2    27.8 2805.98    44.5 2802.68   128.1 2794.39   149.9 2790.29
   171.7  2784.1   189.2 2781.91   258.9 2779.06     320  2778.9   437.7 2780.62
   482.3 2782.45   529.3 2781.81   590.4 2777.96   655.7 2775.63   786.6  2774.7
   804.6 2775.92   825.9 2774.62   853.3 2775.65     934 2773.87     939 2771.87
   943.8 2767.94   947.6 2766.72   958.4 2766.44  966.25 2768.01   982.1 2773.32
   987.6  2777.4  1007.9 2797.07  1030.9 2809.07  1058.2 2817.61  1089.5 2824.84
#Mann= 4 ,-1,0
       0     .05       0     770     .06       0   943.8    .045       0
  966.25      .1       0
Bank Sta=943.8,966.25
XS Rating Curve= 0 ,0
Exp/Cntr(USF)=0,0
Exp/Cntr=0.5,0.3

Type RM Length L Ch R = 1 ,1077    ,73.7,81,81
BEGIN DESCRIPTION:
structure xs 3
END DESCRIPTION:
XS GIS Cut Line= 4
2309449.47329045499718.5997741462309771.62892166500494.009115912
 2309553.6921886500749.5673341552309699.82184594501038.366867475
#Sta/Elev= 30
       0 2813.82    43.8 2802.61   132.6 2793.35   145.7 2790.88   167.4 2784.06
     189 2781.09   325.8 2778.24   496.6 2781.62     561 2780.31   587.5  2777.5
   668.1  2774.5   793.5 2773.55   817.1 2775.19   833.3 2773.71   985.8 2770.42
  1006.8 2767.48  1015.7 2763.59  1022.6 2761.78  1043.6 2761.41  1048.4 2763.63
  1059.4 2769.65  1064.6 2770.55  1106.7 2772.71  1122.4  2776.3    1148 2777.95
  1165.5 2782.85  1206.5 2780.37  1246.8 2780.48  1370.6 2776.43  1499.2 2776.08
#Mann= 6 ,-1,0
       0     .05       0     750     .06       0  1015.7    .045       0
  1048.4     .06       0 1275.54      .1       0 1345.54     .05       0
#XS Ineff= 2 , 0
            1008 2773.44  1056.1         2769.58
Permanent Ineff=
       F       F
Bank Sta=1015.7,1048.4
XS Rating Curve= 0 ,0
Exp/Cntr=0.5,0.3

Type RM Length L Ch R = 1 ,996     ,144.1,128,111.5
BEGIN DESCRIPTION:
structure xs 2
END DESCRIPTION:
XS GIS Cut Line= 4
2309406.06201416499742.246835479  2309706.958552500484.112437377
2309478.69221295500736.5888426852309663.72629081501039.214670965
#Sta/Elev= 30
       0  2812.2    13.1 2808.54    50.6 2801.19   111.1 2795.05   128.3 2790.78
     137 2789.92   158.6 2783.22   188.8 2779.96   282.3 2778.38   341.7 2775.37
   473.7 2779.47   534.1 2779.17   577.3 2776.02   616.1 2775.84   676.4 2773.22
   800.6 2771.74   956.2 2766.81   967.5 2765.64   981.7 2758.78   990.7 2757.49
  1007.2 2757.33  1024.2 2758.75  1033.9 2760.61  1050.1 2765.55  1134.6 2763.34
  1146.3 2763.86  1174.4 2767.72  1235.8 2767.32  1337.4 2771.411495.643 2773.24
#Mann= 11 ,-1,0
       0     .05       0     770     .06       0  820.56     .05       0
  830.56     .06       0  970.56      .1       0   981.7    .045       0
  1024.2      .1       0 1100.56     .06       0 1120.56     .05       0
 1180.93     .06       0 1340.93     .05       0
#XS Ineff= 2 , 0
             965    2769  1046.5            2769
Permanent Ineff=
       F       F
Bank Sta=981.7,1024.2
XS Rating Curve= 0 ,0
Exp/Cntr(USF)=0,0
Exp/Cntr=0.5,0.3

Type RM Length L Ch R = 1 ,868     ,222.2,210.9,196
XS GIS Cut Line= 4
2309255.37878984499861.6471400672309471.13621811500469.391346398
2309420.07911676500780.6749642752309602.89647964500986.550372924
#Sta/Elev= 30
       0 2794.99    72.3 2786.63    80.2 2785.11   101.4  2778.4   122.6    2775
   317.8 2773.32   402.7 2770.17   479.1 2770.87   507.7 2769.79   520.3 2770.66
   551.6 2769.05   636.1 2768.82   713.6 2765.38   786.6 2763.72   790.6 2763.29
   794.7  2761.6     804 2755.92   814.4  2754.7     823  2754.8   827.1 2755.92
   835.3 2761.49   851.4 2762.64   866.7 2762.13   908.5  2760.7  1008.9 2766.09
  1025.2 2764.76  1078.7 2763.85  1116.2 2765.45  1171.3 2768.34  1235.7 2769.92
#Mann= 6 ,-1,0
       0     .05       0     804    .045       0   827.1      .1       0
   866.7     .05       0  1025.2     .06       0  1116.2     .05       0
Bank Sta=804,827.1
XS Rating Curve= 0 ,0
Exp/Cntr(USF)=0,0
Exp/Cntr=0.3,0.1

Type RM Length L Ch R = 1 ,657     ,165.1,164.6,162.9
XS GIS Cut Line= 3
2308947.77194024500049.3096201652309350.20209494500877.961334902
2309644.35440003501052.273811991
#Sta/Elev= 30
       0 2799.83    27.1 2783.88    55.9 2768.88    66.1 2765.63      75 2764.53
   111.2 2765.22   226.6 2763.71   275.6  2764.5     320 2762.29   355.6  2763.3
   452.2 2763.58   480.1 2760.16   511.2 2759.73     527 2758.69   631.3 2760.42
   635.7 2759.17  651.03 2750.86   655.7 2749.78   671.3 2749.38   681.8 2750.91
   706.9 2757.85   773.6 2757.18   806.7 2756.86   840.3  2761.7   859.2 2762.49
   927.9 2762.08   943.2 2760.17     956 2760.02  1100.2 2764.84  1263.1 2772.55
#Mann= 6 ,-1,0
       0     .05       0  651.03    .045       0   681.8      .1       0
   773.6     .05       0     990     .06       0 1119.63     .05       0
Bank Sta=651.03,681.8
XS Rating Curve= 0 ,0
Exp/Cntr(USF)=0,0
Exp/Cntr=0.3,0.1

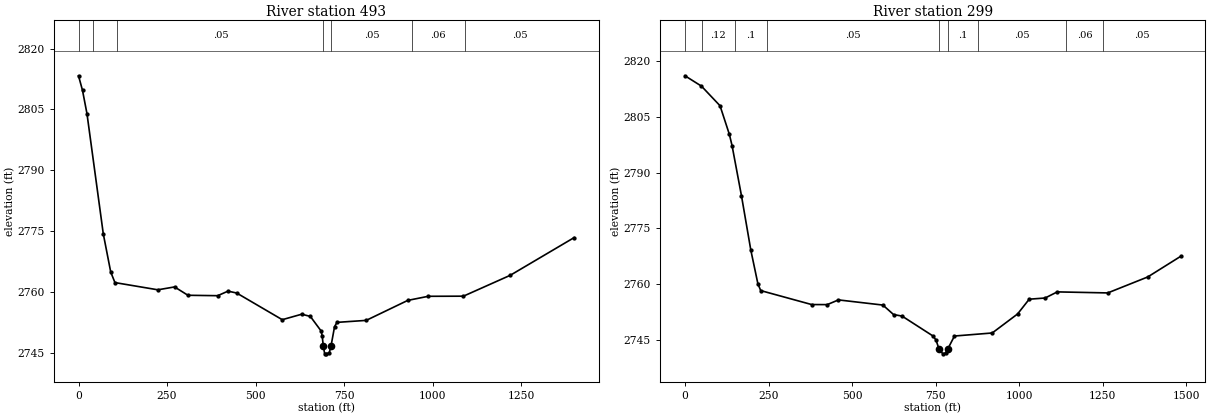
Type RM Length L Ch R = 1 ,493     ,191.2,193.1,193.3
XS GIS Cut Line= 4
2308873.83721756500082.3924527812309009.35894778500512.216405294
2309197.67867749500954.2230436282309647.86176119501085.287014079
#Sta/Elev= 30
       0 2813.29    11.3 2809.68    23.9 2803.95      70  2774.3      91 2764.89
   102.9 2762.29   224.1 2760.51   271.3 2761.22   309.1 2759.16   393.1 2759.06
   422.3 2760.18   446.7 2759.72   575.5 2753.14   630.4 2754.49   654.8 2753.95
   685.3 2750.35   688.3 2749.13   691.4 2746.66   695.2 2744.77   699.6 2744.72
   708.3 2744.99  713.35 2746.71   723.2 2751.42     730 2752.48   812.6 2752.97
     930  2757.9   987.9 2758.91  1087.2 2758.94  1219.5 2764.09    1400 2773.39
#Mann= 7 ,-1,0
       0     .05       0      40     .12       0     110     .05       0
   691.4    .045       0  713.35     .05       0  941.13     .06       0
 1091.13     .05       0
Bank Sta=691.4,713.35
XS Rating Curve= 0 ,0
Exp/Cntr=0.3,0.1

Type RM Length L Ch R = 1 ,299     ,152.4,153.2,153.7
XS GIS Cut Line= 4
2308749.66048273 500068.356120862308741.97474741500264.342371556
2308970.62537322500931.0799106882309529.76261786501092.480352438
#Sta/Elev= 30
       0 2816.06    49.3 2813.27   104.9 2807.98   132.9 2800.25   140.9 2797.23
     169 2783.74     197 2769.09   218.2    2760   226.6 2758.19   378.9 2754.43
   425.6 2754.41   459.2 2755.68   592.1 2754.29   624.1 2751.73   649.5 2751.32
   742.5 2745.93     751 2744.87  760.29 2742.41   771.6 2741.15   780.6 2741.43
     786 2742.43   806.3 2745.95   919.3 2746.77   995.1 2751.89  1029.9 2755.87
  1077.5 2756.19  1113.9 2757.84  1264.8 2757.56  1384.5 2761.861482.958 2767.41
#Mann= 9 ,-1,0
       0     .05       0      50     .12       0     150      .1       0
  246.14     .05       0  760.29    .045       0     786      .1       0
  876.14     .05       0 1140.99     .06       0 1250.99     .05       0
Bank Sta=760.29,786
XS Rating Curve= 0 ,0
Exp/Cntr(USF)=0,0
Exp/Cntr=0.3,0.1