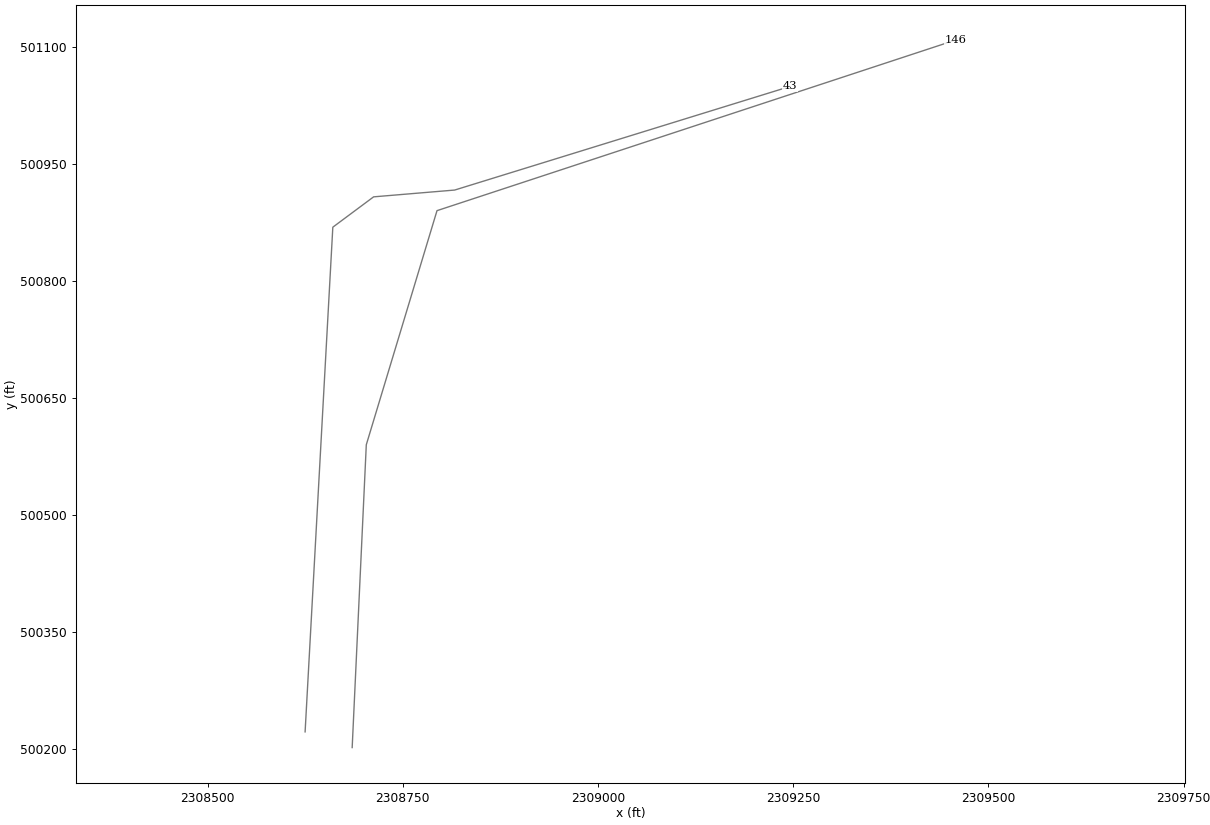
HEC-RAS study STONYRB.prj: STONYRB

--- STONYRB.g01 (geometry) --- (continued)

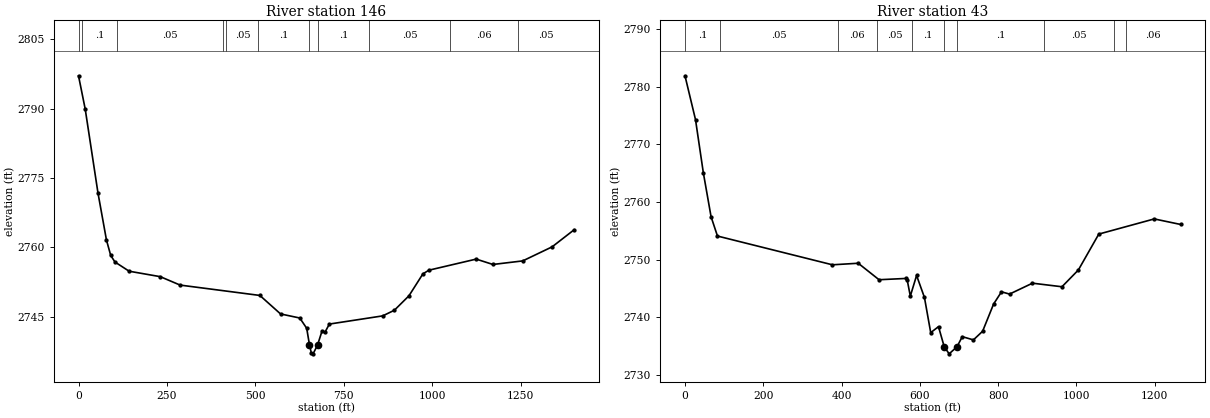
Type RM Length L Ch R = 1 ,146     ,116.6,103.1,90.3
XS GIS Cut Line= 4
2308685.06465409500202.2299744772308703.15364296500590.138291352
2308793.72768653500890.0197893252309458.35904321501108.664743306
#Sta/Elev= 30
       0  2797.1   18.97 2789.89   55.01 2771.76   79.03 2761.57   91.05 2758.24
  103.06 2756.82   143.1 2754.83   231.2 2753.65  287.26 2751.83  512.68 2749.59
  571.18 2745.59   625.5 2744.71  645.11 2742.49  652.95  2738.9  657.95 2737.22
  663.11 2736.96  675.64 2738.83  688.18 2741.84  696.53  2741.6   709.2  2743.4
  859.97 2745.17  892.98 2746.39  934.17 2749.51  973.66 2754.26  990.51 2755.05
 1124.28 2757.45 1171.58 2756.29 1255.79 2757.06 1338.91  2760.1 1401.26  2763.8
#Mann= 11 ,-1,0
       0     .12       0      10      .1       0     110     .05       0
  408.33     .06       0  418.33     .05       0  508.33      .1       0
  652.95    .045       0  675.64      .1       0  821.59     .05       0
 1051.59     .06       0 1241.59     .05       0
Bank Sta=652.95,675.64
XS Rating Curve= 0 ,0
Exp/Cntr(USF)=0,0
Exp/Cntr=0.3,0.1

Type RM Length L Ch R = 1 ,43      ,,,
XS GIS Cut Line= 5
2308624.76802452500222.3288509992308660.27603971500868.842712458
2308712.53311867500907.7005404012308816.37731403 500916.41005356
2309245.82330905501049.062638606
#Sta/Elev= 30
       0 2781.89    26.9 2774.28    46.9 2765.06    66.7 2757.42      83 2754.08
   376.7 2749.09   442.6 2749.36   495.8  2746.5   563.7 2746.72   567.7 2746.47
   575.7 2743.66   591.7 2747.24   611.8 2743.42   627.8 2737.32   647.7 2738.36
   662.3 2734.87   674.9 2733.64     695 2734.87   708.4 2736.62   736.9 2736.06
   760.4 2737.56   788.5 2742.29   808.6  2744.4   829.2 2744.01   887.8  2745.9
   963.1 2745.28    1005 2748.19  1057.2 2754.42  1198.9 2757.051266.285 2756.09
#Mann= 10 ,-1,0
       0      .1       0      90     .05       0     390     .06       0
     490     .05       0     580      .1       0   662.3    .045       0
     695      .1       0  916.82     .05       0 1096.82     .07       0
 1126.82     .06       0
Bank Sta=662.3,695
XS Rating Curve= 0 ,0
Exp/Cntr(USF)=0,0
Exp/Cntr=0.3,0.1
LCMann Table=0

Chan Stop Cuts=-1
Use User Specified Reach Order=0
Composite Channel Slope=5